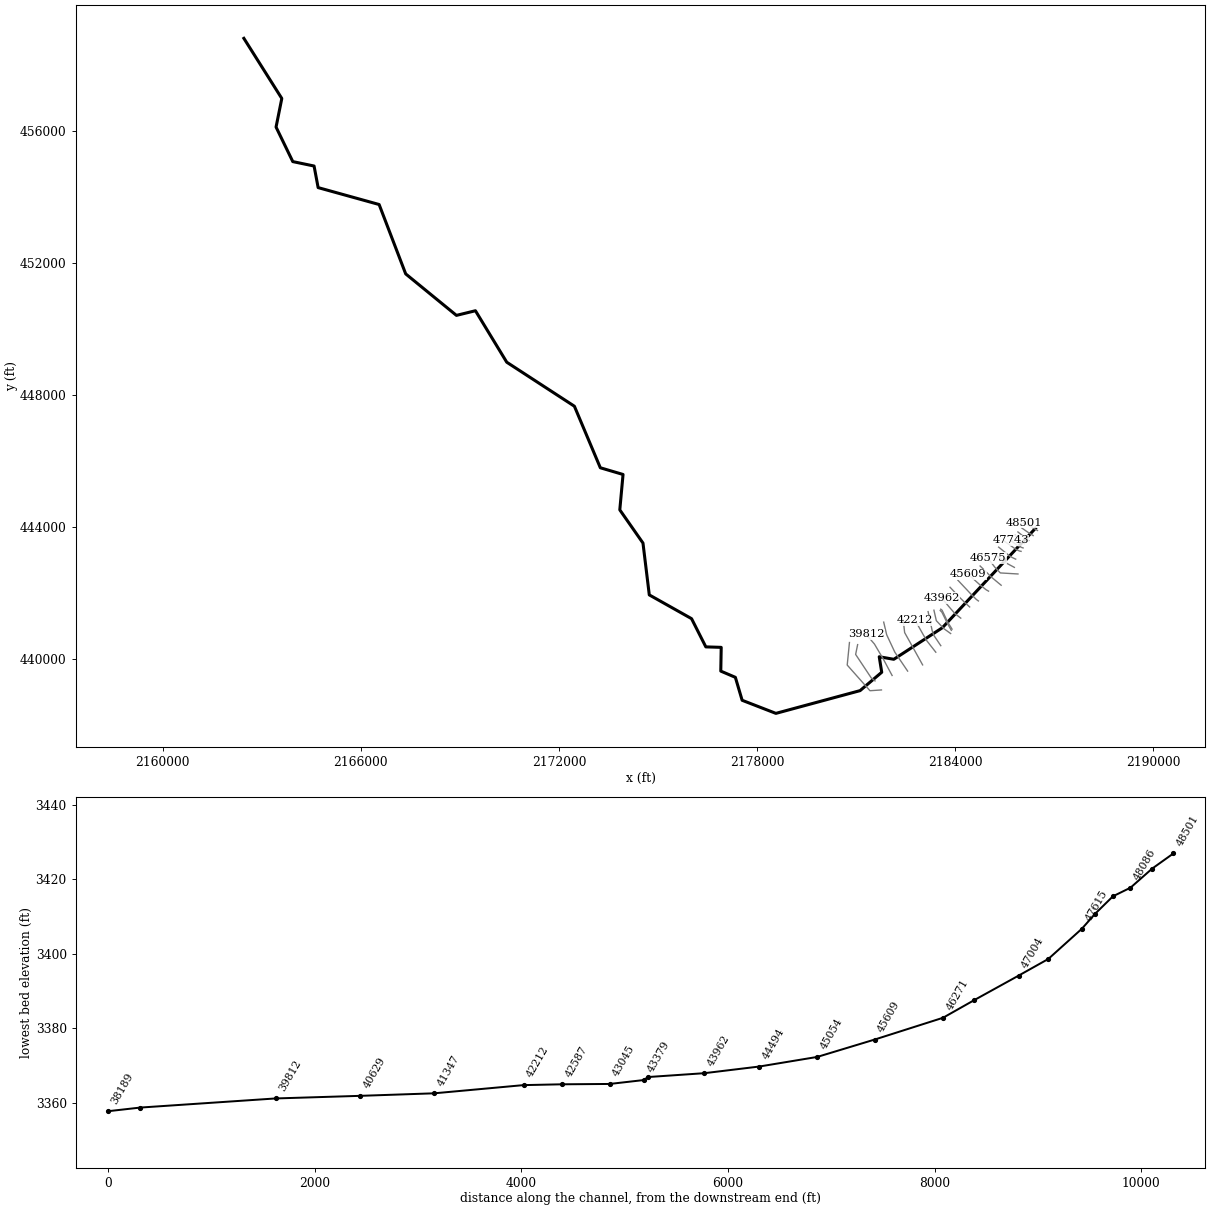
--- SFCRANBRYRV.prj (project) ---

Proj Title=SFCRANBRYRV
Current Plan=p01
Default Exp/Contr=0,0
English Units
Geom File=g01
Flow File=f01
Plan File=p01
Background Map Layer=Inundation Boundary (01pct Value_0)
Background Map Layer=QC
BEGIN DESCRIPTION:
----------MODEL BY WOOD PLC 2021----------
Stream Name: South Fork Cranberry River
Flood Zone: Approximate
Pocahontas County, WV
HEC-RAS Version: RAS 6.1
Vertical Datum: NAVD88
Projection: NAD 1983 StatePlane West Virginia S FIPS 4702 (US Feet)
Terrain: 1-meter LIDAR (FEMA Region III 3DEP collected 2016-2018)
Land Use: 2019 NLCD
Hydrologic Method:
Gage-Weighted WV 2010 RRE
Model Notes:
Model extends beyond county boundary on the downstream end
END DESCRIPTION:
DSS Export Rating Curves= 0
DSS Export Rating Curve Sorted= 0
DSS Export Volume Flow Curves= 0
DXF Filename=..\..\..\..\..\..\Users\brandon.cramer\Wood PLC\Chantilly CTP - Pocahontas\Hydraulics\Models\Approximate\SFCRNBRYRV\SFCRANBRYRV.
DXF OffsetX= 0
DXF OffsetY= 0
DXF ScaleX= 0
DXF ScaleY= 0

--- SFCRANBRYRV.p01 (plan) ---

Plan Title=Floodplain
Program Version=6.10
Short Identifier=Floodplain
Geom File=g01
Flow File=f01
Subcritical Flow
K Sum by GR= 0
Std Step Tol= 0.01
Critical Tol= 0.01
Num of Std Step Trials= 20
Max Error Tol= 0.3
Flow Tol Ratio= 0.001
Split Flow NTrial= 30
Split Flow Tol= 0.02
Split Flow Ratio= 0.02
Log Output Level= 0
Friction Slope Method= 1
Unsteady Friction Slope Method= 2
Unsteady Bridges Friction Slope Method= 1
Parabolic Critical Depth
Global Vel Dist= 0 , 0 , 0
Global Log Level= 0
CheckData=True
Encroach Param=-1 ,0,0, 0
Mapping Interval=1HOUR
Computation Time Step Use Courant=        0
Computation Time Step Use Time Series=    0
Computation Time Step Count To Double=0
Computation Time Step Max Doubling=0
Computation Time Step Max Halving=0
Computation Time Step Residence Courant=0
Run HTab= 0
Run UNet= 0
Run Sediment= 0
Run PostProcess= 0
Run WQNet= 0
Run RASMapper=-1
UNET Theta= 0
UNET Theta Warmup= 0
UNET ZTol= 0
UNET ZSATol= 0
UNET MxIter= 0
UNET Max Iter WO Improvement= 0
UNET MaxInSteps= 0
UNET DtIC= 0
UNET DtMin= 0
UNET MaxCRTS= 0
UNET WFStab= 0
UNET SFStab= 0
UNET WFX= 1
UNET SFX= 1
UNET Gravity=32.174
UNET 1D Methodology=Finite Difference
UNET DSS MLevel= 1
UNET Pardiso=0
UNET DZMax Abort= 0
UNET Use Existing IB Tables= 0
UNET Froude Reduction=False
UNET Froude Limit= 0
UNET Froude Power= 0
UNET D1 Cores= 0
UNET WindReference=Eulerian
UNET WindDragFormulation=Hsu (1988)
UNET D2 Coriolis=0
UNET D2 Cores= 0
UNET D2 Theta= 1
UNET D2 Theta Warmup= 1
UNET D2 Z Tol= 0.01
UNET D2 Volume Tol= 0.01
UNET D2 Max Iterations= 20
UNET D2 Equation= 0
UNET D2 RampUpFraction=0.1
UNET D2 TimeSlices= 1
UNET D2 Turbulence Formulation=Non-Conservative (original)
UNET D2 Eddy Viscosity=0.3
UNET D2 Transverse Eddy Viscosity=0.1
UNET D2 Smagorinsky Mixing=0
UNET D2 BCVolumeCheck=0
UNET D2 Cores=0
UNET D2 SolverType=PARDISO (Direct)
UNET D2 Minimum Iterations= 2147483647
UNET D2 Maximum Iterations= 2147483647
UNET D2 Restart Number= 10
UNET D2 Relaxation Coeff=1.3
UNET D2 SOR Precondition Iterations= 10
UNET D2 ILUT Maximum Fill= 8
UNET D2 ILUT Tolerance=1E-08
UNET D1D2 MaxIter= 0
UNET D1D2 ZTol=0.01
UNET D1D2 QTol=0.1
UNET D1D2 MinQTol=1
Write IC File= 0
Write IC File at Fixed DateTime=0
Write IC File at Sim End=0
Echo Input=False
Echo Parameters=False
Echo Output=False
Write Detailed= 0
HDF Write Warmup=0
HDF Write Time Slices=0
HDF Flush=0
HDF Compression= 1
HDF Chunk Size= 1
HDF Spatial Parts= 1
HDF Use Max Rows=0
HDF Fixed Rows= 1
Calibration Method= 0
Calibration Iterations= 20
Calibration Max Change=0.05
Calibration Tolerance=0.2
Calibration Maximum=1.5
Calibration Minimum=0.5
Calibration Optimization Method= 1
WQ AD Non Conservative
WQ ULTIMATE=-1
WQ Max Comp Step=1HOUR
WQ Output Interval=15MIN
WQ Output Selected Increments= 0
WQ Output face flow=0
WQ Output face velocity=0
WQ Output face area=0
WQ Output face dispersion=0
WQ Output cell volume=0
WQ Output cell surface area=0
WQ Output cell continuity=0
WQ Output cumulative cell continuity=0
WQ Output face conc=0
WQ Output face dconc_dx=0
WQ Output face courant=0
WQ Output face peclet=0
WQ Output face adv mass=0
WQ Output face disp mass=0
WQ Output cell mass=0
WQ Output cell source sink temp=0
WQ Output nsm pathways=0
WQ Output nsm derived pathways=0
WQ Create Restart=0
WQ Fixed Restart=0
WQ System Summary=0
WQ Write To DSS=0
Sorting and Armoring Iterations= 10
XS Update Threshold= 0.02
Bed Roughness Predictor= 0
Hydraulics Update Threshold= 0.02
Energy Slope Method= 1
Volume Change Method= 1
Sediment Retention Method= 0
Sediment TS Multiplier= 1
Warm Up Method= 0
XS Weighting Method= 0
Number of US Weighted Cross Sections= 1
Number of DS Weighted Cross Sections= 1
Upstream XS Weight=0
Main XS Weight=1
Downstream XS Weight=0
Number of DS XS's Weighted with US Boundary= 1
Upstream Boundary Weight= 1
Weight of XSs Associated with US Boundary= 0
Number of US XS's Weighted with DS Boundary= 1
Downstream Boundary Weight= 0.5
Weight of XSs Associated with DS Boundary= 0.5
Percentile Method= 0
Sediment Output Level= 3
Mass or Volume Output= 0
Output Increment Type= 1
Profile and TS Output Increment= 1
Transport Output Increment 1
XS Output Flag= 0
XS Output Increment= 10
Read HDF5 Sediment Hotstart= 0
Sediment Hotstart Type= 0
Write Gradation File= 0
Read Gradation Hotstart= 0
Write HDF5 File= 1
Write Binary Output= 1
Write DSS Sediment File= 0
DSS Sediment Output Type= 1
SV Curve= 0
Specific Gage Flag= 0
Subcell Erosion Methods= 0
Subcell Deposition Methods= 0
Advection Scheme= 1
Matrix Solver= 0
Implicit Weighting Factor= 1
Maximum Outer Loop Convergence Iterations= 5
Convergence Maximum Absolute= 0.001
Convergence RMSE= 0.0001
Grain Fractions Max Abs Error= 0.001
Max Subgrid Regions= 1
Max Subgrid Length Scale= 3.402823E+38
Initial Layer Thickness= 3.402823E+38
Min Layer Thickness= 3.402823E+38
Max Layer Thickness= 3.402823E+38
Number of Layers= 5

--- SFCRANBRYRV.f01 (steady flow) ---

Flow Title=Flow
Program Version=6.10
Number of Profiles= 6
Profile Names=01pct,10pct,04pct,02pct,0_2pct,01plus
River Rch & RM=CRANBRYRVSF,Main            ,48501
     629     333     443     533     877     930
River Rch & RM=CRANBRYRVSF,Main            ,46271
     743     397     525     630    1030    1100
River Rch & RM=CRANBRYRVSF,Main            ,42587
     845     453     598     718    1170    1250
River Rch & RM=CRANBRYRVSF,Main            ,38501
     945     509     671     803    1310    1400
River Rch & RM=CRANBRYRVSF,Main            ,35767
    1050     566     744     891    1450    1550
River Rch & RM=CRANBRYRVSF,Main            ,34192
    1610     884    1150    1370    2200    2380
River Rch & RM=CRANBRYRVSF,Main            ,29481
    1790     987    1280    1530    2440    2640
River Rch & RM=CRANBRYRVSF,Main            ,24561
    1990    1100    1430    1700    2710    2940
River Rch & RM=CRANBRYRVSF,Main            ,20126
    2310    1290    1670    1980    3140    3410
River Rch & RM=CRANBRYRVSF,Main            ,16638
    2580    1440    1870    2210    3500    3810
River Rch & RM=CRANBRYRVSF,Main            ,8694
    2950    1660    2140    2530    3990    4360
River Rch & RM=CRANBRYRVSF,Main            ,384
    4220    2410    3080    3630    5670    6230
Boundary for River Rch & Prof#=CRANBRYRVSF,Main            , 1
Up Type= 0
Dn Type= 1
Dn Known WS=3169.3
Boundary for River Rch & Prof#=CRANBRYRVSF,Main            , 2
Up Type= 0
Dn Type= 1
Dn Known WS=3167.9
Boundary for River Rch & Prof#=CRANBRYRVSF,Main            , 3
Up Type= 0
Dn Type= 1
Dn Known WS=3168.3
Boundary for River Rch & Prof#=CRANBRYRVSF,Main            , 4
Up Type= 0
Dn Type= 1
Dn Known WS=3169
Boundary for River Rch & Prof#=CRANBRYRVSF,Main            , 5
Up Type= 0
Dn Type= 1
Dn Known WS=3170.2
Boundary for River Rch & Prof#=CRANBRYRVSF,Main            , 6
Up Type= 0
Dn Type= 1
Dn Known WS=3170.5
DSS Import GetInterval= 0
DSS Import GetPeak= 0
DSS Import FillOption= 0

--- SFCRANBRYRV.g01 (geometry) ---

Geom Title=Geometry
Program Version=6.10

River Reach=CRANBRYRVSF     ,Main
Reach XY= 30
2186425.71100003443956.9980000112183607.20800005440945.548999995
2182138.70700002439990.4249999972181697.16500001440067.889000013
2181772.35300002439597.2320000082181116.86399999439040.915999994
2178567.75600003438351.7039999962177545.86100003438748.522000015
2177340.63600002439443.741999999     2176899.009439632.773000017
2176912.11700003440352.1690000152176446.11700003440366.555000022
      2176013.94441221.5310000032174734.27200001441941.387000009
2174543.05500004443512.4490000012173841.15500002444518.165000007
     2173939.756445590.7380000052173251.77900004445793.866999999
2172466.53299998447658.5690000212170418.06599998448992.258000001
      2169470.19 450552.15700002     2168894.641450411.373000011
2167358.21800004451668.5350000112166553.83300003453770.606000006
2164706.83700003 454283.086000012164583.81300004454937.164000005
2163939.18200001455071.186000004      2163432.58456116.952999994
2163606.70499998456983.8680000162162457.92732565 458806.10728763

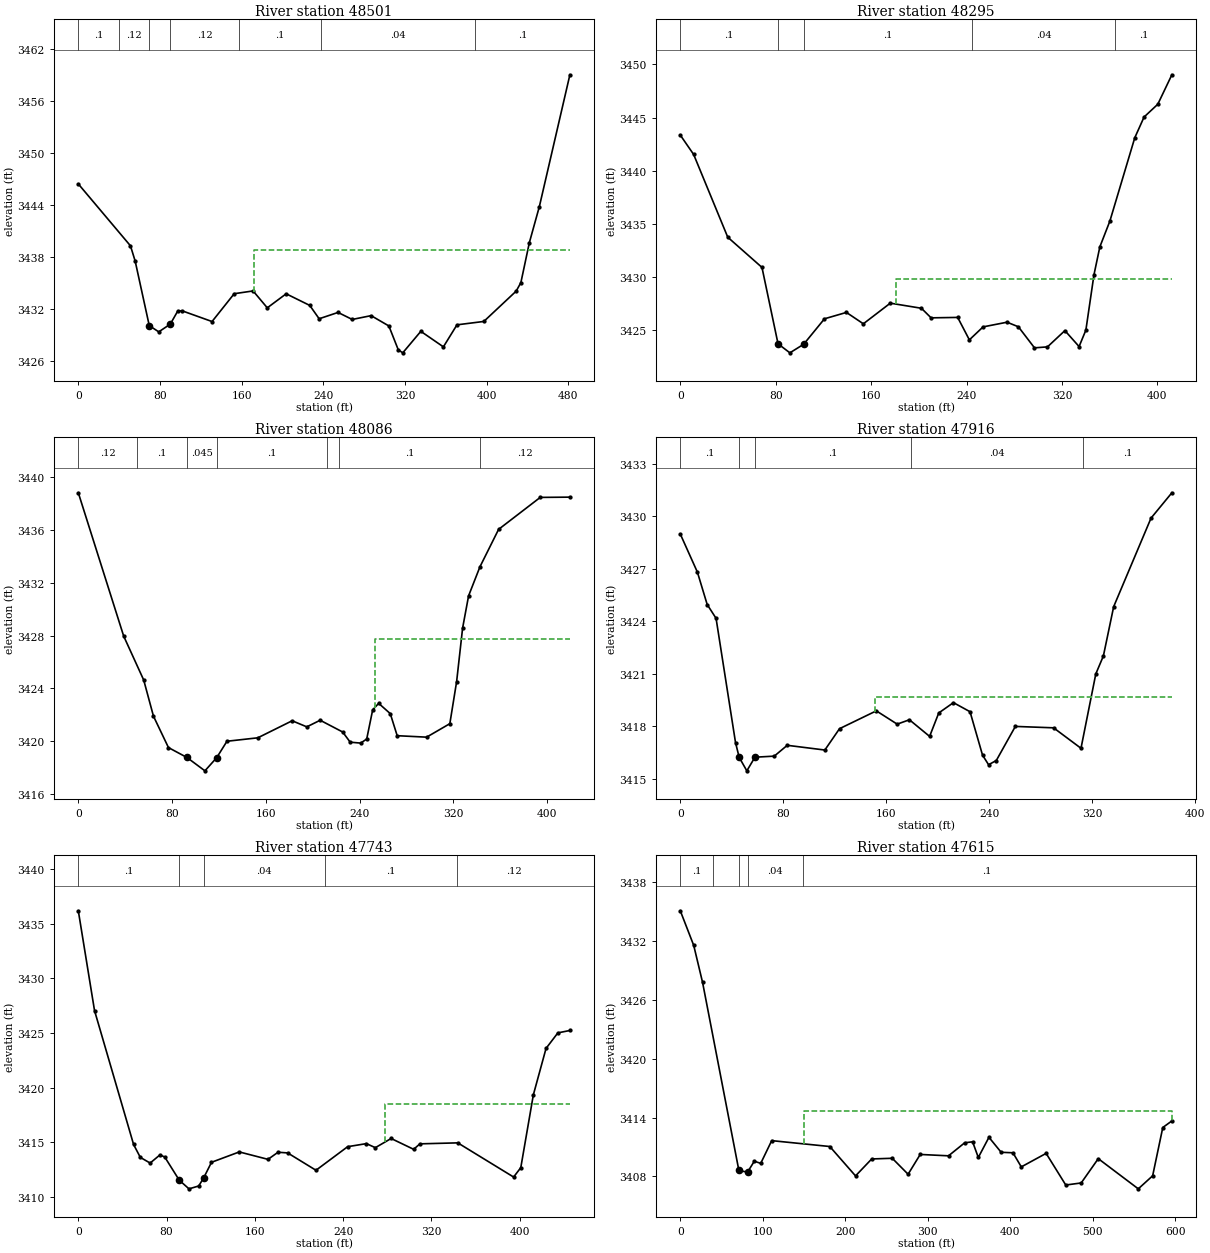
Type RM Length L Ch R = 1 ,48501   ,206,206.1,205.1
XS GIS Cut Line= 5
2186488.42032346443894.4145813562186438.78804417443922.990742159
2186238.75491855444038.7993938342186133.47432612444088.431673123
2186065.79394527444124.527876243
#Sta/Elev= 30
       0 3446.44    51.1  3439.3    55.7 3437.54    69.5  3430.1    78.8 3429.38
    90.1 3430.27    97.3 3431.76   101.6 3431.81     131 3430.57   152.7 3433.78
   171.2  3434.1   185.1 3432.15   203.6 3433.77   226.7 3432.43   235.9 3430.89
   254.4 3431.62   268.3 3430.81   286.8 3431.25   304.2 3430.06   313.4 3427.31
   317.8 3426.96   335.5 3429.44   357.6 3427.65   370.9 3430.19   397.2 3430.58
   428.9 3434.08   433.5 3435.06   441.8 3439.67   451.6 3443.83   481.5 3459.03
#Mann= 7 ,-1,0
       0      .1       0      40     .12       0    69.5    .045       0
    90.1     .12       0  157.27      .1       0  237.27     .04       0
  388.41      .1       0
#XS Ineff= 2 , 0
                          172.04         3438.86
Permanent Ineff=
       F       F
Bank Sta=69.5,90.1
XS Rating Curve= 0 ,0
Exp/Cntr(USF)=0,0
Exp/Cntr=0.3,0.1

Type RM Length L Ch R = 1 ,48295   ,209.9,209.6,205.2
XS GIS Cut Line= 4
2186357.57158715443739.5017096352186297.41124862443778.605929681
2186184.61061387443849.2943274572186014.65765752443968.110996059
#Sta/Elev= 30
       0 3443.35    11.2 3441.53    39.8 3433.75    68.5 3430.91   81.963423.729
    91.9 3422.88   103.5 3423.69   120.9 3426.08   139.3 3426.68   153.5 3425.61
   176.1 3427.55   202.2 3427.07   210.3 3426.17   232.6 3426.21   242.4  3424.1
   253.9 3425.32     274 3425.76   283.5 3425.33     297 3423.35   307.9 3423.44
   322.5 3424.97   334.4 3423.47   340.1 3425.02   346.9 3430.23   351.8 3432.84
   360.2 3435.26   381.1  3443.1   388.9 3445.05   400.4 3446.25   412.2 3449.02
#Mann= 5 ,-1,0
       0      .1       0   81.96    .045       0   103.5      .1       0
  244.87     .04       0  364.87      .1       0
#XS Ineff= 2 , 0
                          181.26         3429.78
Permanent Ineff=
       F       F
Bank Sta=81.96,103.5
XS Rating Curve= 0 ,0
Exp/Cntr(USF)=0,0
Exp/Cntr=0.3,0.1

Type RM Length L Ch R = 1 ,48086   ,166.2,169.8,169.5
XS GIS Cut Line= 4
2186222.96282968443585.7920446852186179.34658425443618.880230878
2186074.06599182443707.6167302132185896.59299315443848.993525764
#Sta/Elev= 30
       0 3438.81    38.7 3427.96    55.8 3424.63    64.1  3421.9    76.9 3419.52
    92.7 3418.77     108 3417.76  118.07 3418.76   126.8    3420   153.1 3420.26
   182.4 3421.55   194.9 3421.09   206.3 3421.59   225.5  3420.7   231.9 3419.93
   240.9 3419.86     246 3420.17   251.1 3422.38   256.2 3422.87   266.1 3422.09
     272 3420.42   297.1 3420.31   316.9 3421.33   322.7 3424.52   327.8 3428.57
   332.9 3431.01   342.6 3433.21   358.5 3436.04     394 3438.46   419.3 3438.48
#Mann= 7 ,-1,0
       0     .12       0      50      .1       0    92.7    .045       0
  118.07      .1       0  212.44     .04       0  222.44      .1       0
  342.44     .12       0
#XS Ineff= 2 , 0
                          252.69         3427.71
Permanent Ineff=
       F       F
Bank Sta=92.7,118.07
XS Rating Curve= 0 ,0
Exp/Cntr(USF)=0,0
Exp/Cntr=0.3,0.1

Type RM Length L Ch R = 1 ,47916   ,164.8,173.3,175.9
XS GIS Cut Line= 4
 2186095.1221103443491.0395114962186071.05797489443507.583604593
2185932.68919627443612.864197025 2185812.3685192443745.216941796
#Sta/Elev= 30
       0 3428.99    13.3 3426.81    20.9 3424.96    27.8 3424.17    42.9 3417.07
   45.75 3416.22    51.7 3415.45      58 3416.23      73 3416.29    83.1 3416.91
   112.3 3416.64   123.7 3417.86   152.3 3418.88   168.5 3418.12     178 3418.37
   193.7 3417.42   200.8 3418.76   212.2 3419.35   225.1 3418.83   234.8 3416.35
   239.5  3415.8   245.5 3416.04   260.3 3417.99     290 3417.91   311.3 3416.74
   322.8 3420.99   328.7 3422.02   336.7 3424.84   365.7  3429.9   381.9 3431.35
#Mann= 5 ,-1,0
       0      .1       0   45.75    .045       0      58      .1       0
   179.2     .04       0  313.07      .1       0
#XS Ineff= 2 , 0
                           151.1         3419.67
Permanent Ineff=
       F       F
Bank Sta=45.75,58
XS Rating Curve= 0 ,0
Exp/Cntr(USF)=0,0
Exp/Cntr=0.3,0.1

Type RM Length L Ch R = 1 ,47743   ,126.5,127.9,128
XS GIS Cut Line= 4
2186053.00987333443364.7028005782186015.40966175443376.734868285
2185884.56092544443436.8952068172185675.50374904443594.816095465
#Sta/Elev= 30
       0  3436.2    14.7 3427.06    50.1  3414.8    56.2 3413.62    65.1  3413.1
    73.9 3413.84    78.3 3413.66    91.5 3411.53   100.3 3410.74   109.1    3411
   113.5 3411.72   120.7 3413.17   145.9 3414.12   171.9 3413.44     181 3414.09
   189.7 3414.03   215.4 3412.44   244.1  3414.6   261.1 3414.88   269.2 3414.51
   283.5 3415.35   303.9 3414.36   309.6 3414.86   343.9 3414.95   394.5 3411.82
     401 3412.68   412.4 3419.35   423.9  3423.6   434.6 3425.02   445.5 3425.24
#Mann= 5 ,-1,0
       0      .1       0    91.5    .045       0   113.5     .04       0
  223.49      .1       0  343.49     .12       0
#XS Ineff= 2 , 0
                          278.03         3418.51
Permanent Ineff=
       F       F
Bank Sta=91.5,113.5
XS Rating Curve= 0 ,0
Exp/Cntr(USF)=0,0
Exp/Cntr=0.3,0.1

Type RM Length L Ch R = 1 ,47615   ,324.7,324.4,324
XS GIS Cut Line= 4
2185992.16623219443261.3848463512185944.78996559 443270.86009967
2185839.20857147443319.5899738812185487.27059105443568.653775406
#Sta/Elev= 30
       0 3435.11    16.3 3431.57      27  3427.8      71 3408.61   81.46 3408.43
    89.7 3409.55    97.5 3409.33   110.8 3411.65   181.2 3411.05   212.4 3408.05
     232 3409.78   256.9 3409.85   276.1 3408.22   290.8 3410.24   325.1  3410.1
   344.7 3411.43   354.3 3411.53   361.2 3409.93   374.1 3411.99   388.9 3410.46
   403.2 3410.41   413.3 3408.97   443.4 3410.35   467.2 3407.12   485.9 3407.33
   506.6 3409.81   555.1 3406.73   572.5 3408.06   584.8 3412.99   595.8 3413.66
#Mann= 5 ,-1,0
       0      .1       0      40     .04       0      71    .045       0
   81.46     .04       0  148.31      .1       0
#XS Ineff= 2 , 0
                          150.23         3414.67
Permanent Ineff=
       F       F
Bank Sta=71,81.46
XS Rating Curve= 0 ,0
Exp/Cntr(USF)=0,0
Exp/Cntr=0.3,0.1

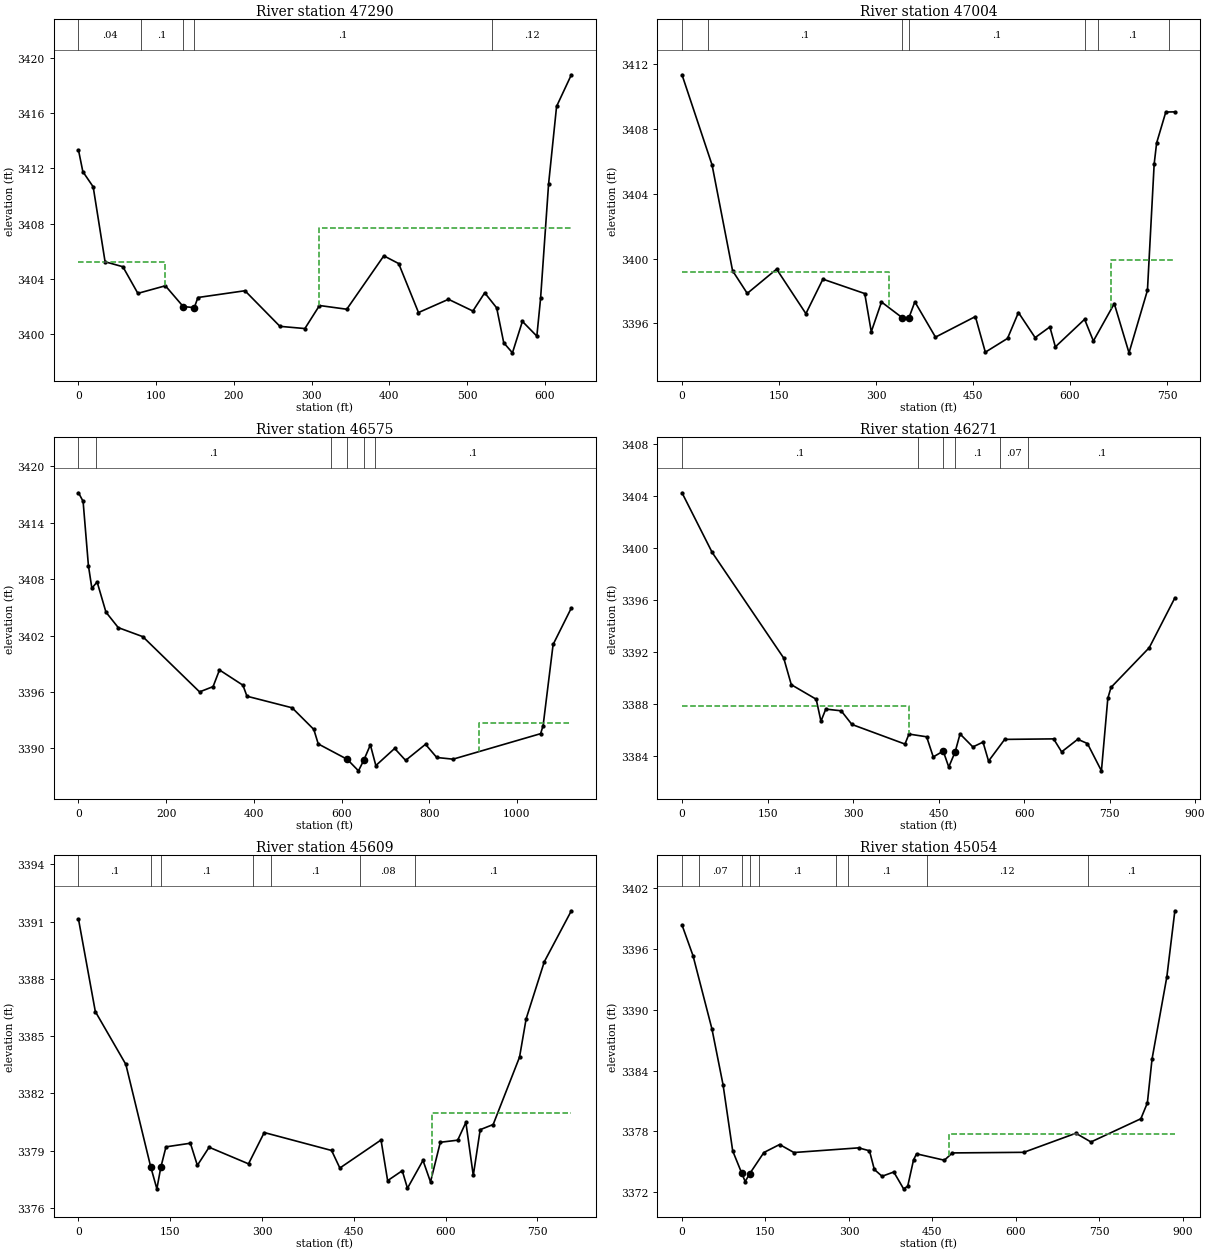
Type RM Length L Ch R = 1 ,47290   ,286.6,286.2,283.2
XS GIS Cut Line= 4
2185829.28211561443024.8043150722185720.99350625443075.940602825
2185633.76101538443130.084907504 2185313.4072127443388.774363193
#Sta/Elev= 30
       0 3413.32     5.6 3411.76    18.9 3410.66    34.2 3405.23    57.1 3404.87
    76.4 3402.94   111.8 3403.49   134.8 3401.98     149 3401.91   153.7 3402.64
   214.2 3403.13   259.2 3400.55   291.3 3400.39   310.1 3402.06   345.2 3401.79
   392.9 3405.66     412  3405.1   437.5 3401.55   476.1 3402.51   507.5 3401.66
   522.7 3402.98   538.1 3401.89   547.2 3399.36   558.4 3398.63   571.2 3400.91
   589.8 3399.84   594.6 3402.57   604.9 3410.86   615.2 3416.49   634.2 3418.78
#Mann= 5 ,-1,0
       0     .04       0      80      .1       0   134.8    .045       0
     149      .1       0  532.43     .12       0
#XS Ineff= 2 , 0
          111.01 3405.19  309.68         3407.68
Permanent Ineff=
       F       F
Bank Sta=134.8,149
XS Rating Curve= 0 ,0
Exp/Cntr(USF)=0,0
Exp/Cntr=0.3,0.1

Type RM Length L Ch R = 1 ,47004   ,420.7,428.6,418
XS GIS Cut Line= 4
2185789.17522326442775.3060222142185548.53386913442903.982301853
2185416.51534846442994.2228096512185159.16278918443199.770632971
#Sta/Elev= 30
       0 3411.35    46.5 3405.78    78.2 3399.25   100.9 3397.85   146.3 3399.35
   191.6  3396.6   217.9 3398.73   282.6 3397.84   292.7 3395.48   308.5 3397.32
   340.2 3396.36   350.8 3396.33   360.1 3397.33     392 3395.15   453.7 3396.42
   469.1 3394.22   503.4 3395.07   520.3 3396.67   546.1 3395.12   568.9 3395.78
   577.4 3394.55   622.6 3396.25   636.2 3394.91   668.5 3397.22   691.3 3394.18
   719.8 3398.04   730.2 3405.84     734 3407.14   748.2 3409.05   762.2 3409.06
#Mann= 7 ,-1,0
       0     .04       0      40      .1       0   340.2    .045       0
   350.8      .1       0   622.8     .12       0   642.8      .1       0
   752.8     .12       0
#XS Ineff= 2 , 0
          319.51  3399.2  663.59         3399.92
Permanent Ineff=
       F       F
Bank Sta=340.2,350.8
XS Rating Curve= 0 ,0
Exp/Cntr(USF)=0,0
Exp/Cntr=0.3,0.1

Type RM Length L Ch R = 1 ,46575   ,305.1,304.2,301.5
XS GIS Cut Line= 4
2185898.63248827 442575.745591382185364.06611587 442607.19067211
2185196.35901865442781.8855650512184986.72514712443057.903495898
#Sta/Elev= 30
       0 3417.17    10.5 3416.26    22.6 3409.44    30.5 3407.03    42.5 3407.69
    62.6 3404.49    90.7 3402.84   146.7 3401.88   276.2 3396.01     307 3396.57
   321.6 3398.34   375.1 3396.72   384.3 3395.55   487.3 3394.32   536.8 3392.02
   546.9 3390.48   613.2 3388.84   638.7 3387.62   650.9 3388.76   665.8 3390.38
   678.3 3388.18   721.2    3390   746.2 3388.73   791.6 3390.44   817.2 3389.04
   854.4 3388.86  1054.2 3391.57  1059.9 3392.43  1082.7 3401.05  1124.3 3404.93
#Mann= 6 ,-1,0
       0     .04       0      40      .1       0  575.49     .12       0
   613.2    .045       0   650.9     .12       0  675.49      .1       0
#XS Ineff= 2 , 0
                          914.29         3392.66
Permanent Ineff=
       F       F
Bank Sta=613.2,650.9
XS Rating Curve= 0 ,0
Exp/Cntr(USF)=0,0
Exp/Cntr=0.3,0.1

Type RM Length L Ch R = 1 ,46271   ,636.4,662.2,641
XS GIS Cut Line= 4
   2185388.82737442234.5909227512185070.44592761442499.484282816
2184978.75207221442596.2722413012184752.06448523442817.865725201
#Sta/Elev= 30
       0 3404.25    52.9 3399.66   178.4 3391.53   191.7 3389.48   235.4 3388.36
   243.7 3386.67   252.2  3387.6   279.2 3387.47     298 3386.42   391.1 3384.91
   398.1 3385.68   429.1 3385.47   440.7 3383.92   458.2 3384.37   467.9 3383.14
   479.2 3384.32   487.7 3385.69   510.2 3384.69     528 3385.06   537.7  3383.6
     566 3385.27   651.8 3385.31   665.9 3384.31   694.2 3385.28   711.2 3384.95
   735.7 3382.85   746.9 3388.43   752.5 3389.27   819.6 3392.33   864.5 3396.16
#Mann= 6 ,-1,0
       0      .1       0  414.17     .08       0   458.2    .045       0
   479.2      .1       0  557.49     .07       0  607.49      .1       0
#XS Ineff= 2 , 0
          397.85 3387.83
Permanent Ineff=
       F       F
Bank Sta=458.2,479.2
XS Rating Curve= 0 ,0
Exp/Cntr(USF)=0,0
Exp/Cntr=0.3,0.1

Type RM Length L Ch R = 1 ,45609   ,552.1,555.4,531.1
XS GIS Cut Line= 4
2185007.68853427442055.1548104162184934.31667924442097.081584722
2184749.14009272442243.8252947922184389.26861326442568.757795663
#Sta/Elev= 30
       0 3391.13    27.5 3386.29    77.4 3383.52   117.9 3378.17   128.1    3377
   134.5 3378.12     143  3379.2   182.9 3379.39   194.3 3378.23   213.5 3379.18
   277.9 3378.31   303.6 3379.95   413.7 3379.01   427.2 3378.09   494.5 3379.56
   505.3 3377.43   529.2 3377.95   537.7 3377.03   563.1 3378.49   575.4 3377.36
   591.4 3379.44   619.8 3379.55   633.2 3380.48   645.3  3377.7   656.6  3380.1
   677.8 3380.37   720.9  3383.9   731.7 3385.91   761.4  3388.9   805.6 3391.57
#Mann= 7 ,-1,0
       0      .1       0   117.9    .045       0   134.5      .1       0
  284.51     .08       0  314.51      .1       0  460.78     .08       0
  550.78      .1       0
#XS Ineff= 2 , 0
                          577.57         3380.97
Permanent Ineff=
       F       F
Bank Sta=117.9,134.5
XS Rating Curve= 0 ,0
Exp/Cntr(USF)=0,0
Exp/Cntr=0.3,0.1

Type RM Length L Ch R = 1 ,45054   ,486.1,559.5,492.3
XS GIS Cut Line= 4
 2184700.2255227441758.1734924162184637.33536124441803.594164581
2184459.14657044441981.7829553812184078.31170383442387.075107004
#Sta/Elev= 30
       0 3398.35    19.8 3395.32    53.8  3388.1    73.8 3382.59    91.1 3376.08
   107.5 3373.86   113.5 3373.06   121.9 3373.85   147.1 3375.92   175.4 3376.71
   201.1 3375.92   317.4 3376.38   336.9 3376.09   345.6 3374.25   359.5 3373.58
   380.6    3374   398.2 3372.34   405.6  3372.6   416.1  3375.2   421.5 3375.79
   471.5 3375.16   485.8 3375.88   614.3 3375.94   707.8 3377.82   734.9 3376.96
   824.6 3379.25   836.3 3380.81   844.7 3385.14   871.3 3393.24   885.7 3399.75
#Mann= 9 ,-1,0
       0      .1       0      30     .07       0   107.5    .045       0
   121.9     .07       0  137.58      .1       0  277.58     .08       0
  297.58      .1       0  439.57     .12       0  729.57      .1       0
#XS Ineff= 2 , 0
                          479.65         3377.77
Permanent Ineff=
       F       F
Bank Sta=107.5,121.9
XS Rating Curve= 0 ,0
Exp/Cntr(USF)=0,0
Exp/Cntr=0.3,0.1

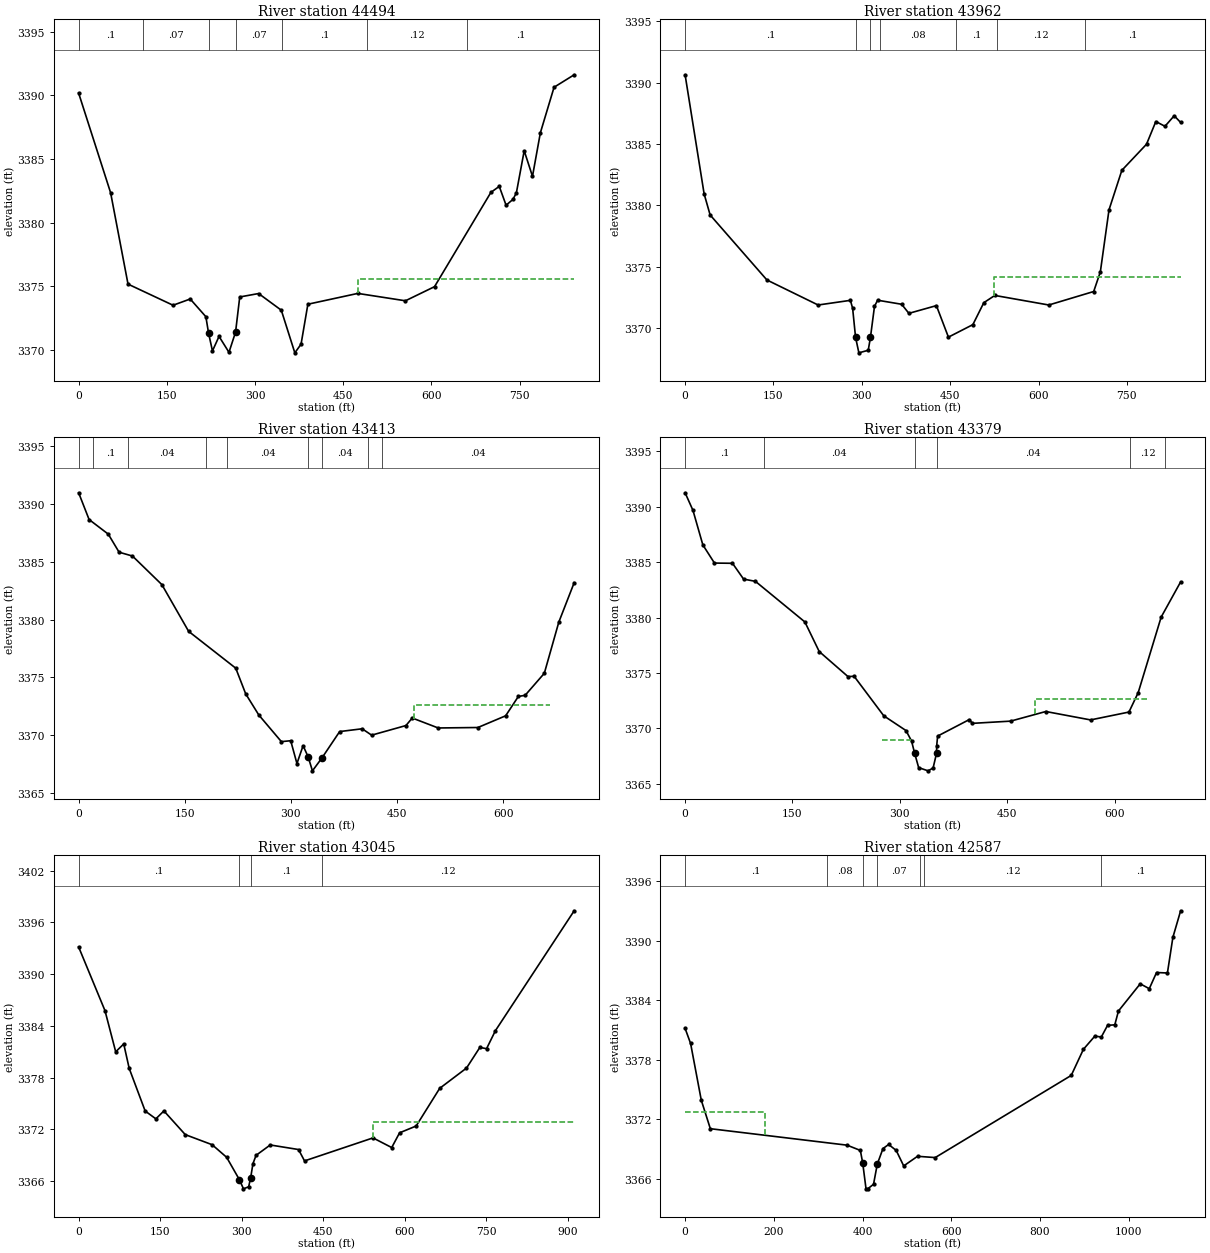
Type RM Length L Ch R = 1 ,44494   ,505.7,532.6,524.6
XS GIS Cut Line= 4
2184434.68928543441576.4908037572184312.40286037 441688.29553524
2184130.72017171441866.4843260392183840.72664943442173.947337616
#Sta/Elev= 30
       0 3390.18    54.4 3382.35      84 3375.17   160.6 3373.51   189.8    3374
   216.4 3372.61  220.973371.323   227.6 3369.92   238.8 3371.06   255.7 3369.81
   266.9  3371.4     274 3374.16   306.1 3374.43   344.7 3373.12   367.7 3369.77
   378.3 3370.45   389.9 3373.59   474.8 3374.44   555.8 3373.86   605.3 3374.97
   701.2 3382.38   715.4 3382.85     727 3381.37   738.7 3381.83   744.5 3382.34
   757.8 3385.65   771.9 3383.64   785.3 3387.06   808.6 3390.64   842.8 3391.62
#Mann= 7 ,-1,0
       0      .1       0     110     .07       0  220.97    .045       0
   266.9     .07       0  345.69      .1       0  490.17     .12       0
  660.17      .1       0
#XS Ineff= 2 , 0
                          475.25         3375.59
Permanent Ineff=
       F       F
Bank Sta=220.97,266.9
XS Rating Curve= 0 ,0
Exp/Cntr(USF)=0,0
Exp/Cntr=0.3,0.1

Type RM Length L Ch R = 1 ,43962   ,522.3,548.5,529.8
XS GIS Cut Line= 4
 2184165.6591503441237.5827114522183990.96425736441373.844727946
2183847.71444514 441538.057927312183589.16600359441845.520938887
#Sta/Elev= 30
       0 3390.65    32.3 3380.94    42.5 3379.22   138.9 3373.92   225.8 3371.88
   280.6 3372.26   284.4 3371.61  289.363369.247     295 3367.98   310.9 3368.19
  314.653369.246   321.5 3371.77   326.8 3372.27   367.6 3371.94   379.9  3371.2
   426.6 3371.83     447 3369.26   488.5 3370.28   507.1 3372.07   525.8 3372.66
   617.4 3371.88   693.6 3372.98   704.9 3374.58   719.6 3379.64   741.4 3382.86
   783.3 3384.99   799.1 3386.84   814.6 3386.45   830.3 3387.31   841.2 3386.76
#Mann= 7 ,-1,0
       0      .1       0  289.36    .045       0  314.65      .1       0
  331.55     .08       0  459.47      .1       0  529.47     .12       0
  679.47      .1       0
#XS Ineff= 2 , 0
                          523.65         3374.18
Permanent Ineff=
       F       F
Bank Sta=289.36,314.65
XS Rating Curve= 0 ,0
Exp/Cntr(USF)=0,0
Exp/Cntr=0.5,0.3

Type RM Length L Ch R = 1 ,43413   ,29.8,34.1,31.5
XS GIS Cut Line= 5
2183902.30013519 440904.578511952183761.54455697441130.962152564
 2183711.2095603 441241.983471262183601.16480608441475.655869144
2183559.17382393441509.248654861
#Sta/Elev= 30
       0 3390.94    14.8 3388.63    41.9 3387.37    57.2 3385.81    76.1 3385.48
   117.7 3383.01   155.5 3378.98   222.1  3375.8   236.2 3373.58   254.7 3371.76
   286.6 3369.46   299.8 3369.54   308.6 3367.57   317.3 3369.11   324.5 3368.14
   330.5 3366.94   343.7 3368.03     369 3370.33   400.8 3370.57   414.2 3370.02
   462.7 3370.85   471.6  3371.5   508.3 3370.64   564.4 3370.68   603.6 3371.69
   621.6 3373.36   631.2 3373.46   658.3 3375.36   678.8 3379.78   700.5 3383.18
#Mann= 9 ,-1,0
       0     .04       0      20      .1       0      70     .04       0
     180      .1       0     210     .04       0   324.5    .045       0
   343.7     .04       0  408.47      .1       0  428.47     .04       0
#XS Ineff= 3 ,-1
  289.55  318.59 3368.59  354.68  392.52 3368.55  473.49  666.23 3372.59
Permanent Ineff=
       F       F       F
Bank Sta=324.5,343.7
XS Rating Curve= 0 ,0
Exp/Cntr(USF)=0,0
Exp/Cntr=0.5,0.3

Type RM Length L Ch R = 1 ,43379   ,316,333.7,340.9
XS GIS Cut Line= 5
2183880.37323124440867.5735557942183744.19344453441108.462468398
2183677.94831629441248.9045655522183593.96635199441418.068236486
2183543.57717342441468.457415062
#Sta/Elev= 30
       0 3391.27      11 3389.68    24.8 3386.56      41 3384.92    66.2  3384.9
    81.7 3383.47    98.2 3383.27   167.3  3379.6   187.3 3376.93   227.4 3374.67
   236.1 3374.69   277.5 3371.12   308.5 3369.79   316.3 3368.84   320.43367.785
   326.2 3366.44   339.4 3366.15   346.4 3366.41  351.16 3367.73   351.43368.427
   352.7 3369.29   396.9 3370.78   401.3 3370.44   454.6 3370.64   503.8 3371.51
   566.3 3370.75   619.9 3371.46   632.8 3373.21   664.9 3380.04   692.1 3383.22
#Mann= 6 ,-1,0
       0      .1       0     110     .04       0   320.4    .045       0
  351.16     .04       0  620.86     .12       0  670.86     .04       0
#XS Ineff= 3 ,-1
  274.92  315.73 3368.91  355.78  402.75    3369     489  644.55 3372.68
Permanent Ineff=
       F       F       F
Bank Sta=320.4,351.16
XS Rating Curve= 0 ,0
Exp/Cntr(USF)=0,0
Exp/Cntr=0.5,0.3

Type RM Length L Ch R = 1 ,43045   ,452.8,457.9,431.3
XS GIS Cut Line= 4
2183859.59369786440770.797957513 2183658.3451812440915.445328868
 2183425.6515838441160.7169585572183353.32789812441478.312273924
#Sta/Elev= 30
       0 3393.15    48.5 3385.76    68.2 3380.99      83  3381.9      93 3379.07
   122.4 3374.12   142.1 3373.21   156.9 3374.13   196.2 3371.38   245.6 3370.21
   272.3 3368.75   295.9 3366.14   303.3 3365.09   312.8 3365.33   316.4 3366.33
   320.7 3368.01   326.5 3368.98   352.5 3370.18   404.6 3369.65   415.6 3368.33
   541.6    3371     576 3369.88   590.5 3371.59     621 3372.38   664.3 3376.75
   713.6  3379.1   738.2  3381.5   750.5 3381.35   766.9 3383.45   911.7 3397.35
#Mann= 4 ,-1,0
       0      .1       0   295.9    .045       0   316.4      .1       0
  447.84     .12       0
#XS Ineff= 2 , 0
                          542.35          3372.9
Permanent Ineff=
       F       F
Bank Sta=295.9,316.4
XS Rating Curve= 0 ,0
Exp/Cntr(USF)=0,0
Exp/Cntr=0.3,0.1

Type RM Length L Ch R = 1 ,42587   ,363.7,375,373.9
XS GIS Cut Line= 4
2183560.86543093440402.8905129792183353.32789812440711.052304127
2183299.87126088440858.8441835552183177.23544603441434.289160903
#Sta/Elev= 30
       0 3381.17    12.4 3379.65    36.5 3373.93    56.9 3371.06   365.2  3369.4
   395.1 3368.87  400.48 3367.58   407.8 3365.02   411.6    3365   424.8 3365.46
   433.3  3367.5   446.1 3369.06   458.9 3369.47   475.9 3368.87   492.8 3367.31
     524 3368.28   563.8 3368.15   870.5 3376.43   897.9 3379.06   923.7 3380.39
   938.3  3380.3   952.3 3381.47   968.7 3381.53   976.9 3382.92    1026 3385.66
  1046.4 3385.17  1062.8  3386.8  1087.3 3386.75  1099.6 3390.34  1117.1 3393.02
#Mann= 7 ,-1,0
       0      .1       0     320     .08       0  400.48    .045       0
   433.3     .07       0  528.69     .08       0  538.69     .12       0
  938.69      .1       0
#XS Ineff= 2 , 0
          180.86 3372.77
Permanent Ineff=
       F       F
Bank Sta=400.48,433.3
XS Rating Curve= 0 ,0
Exp/Cntr(USF)=0,0
Exp/Cntr=0.3,0.1

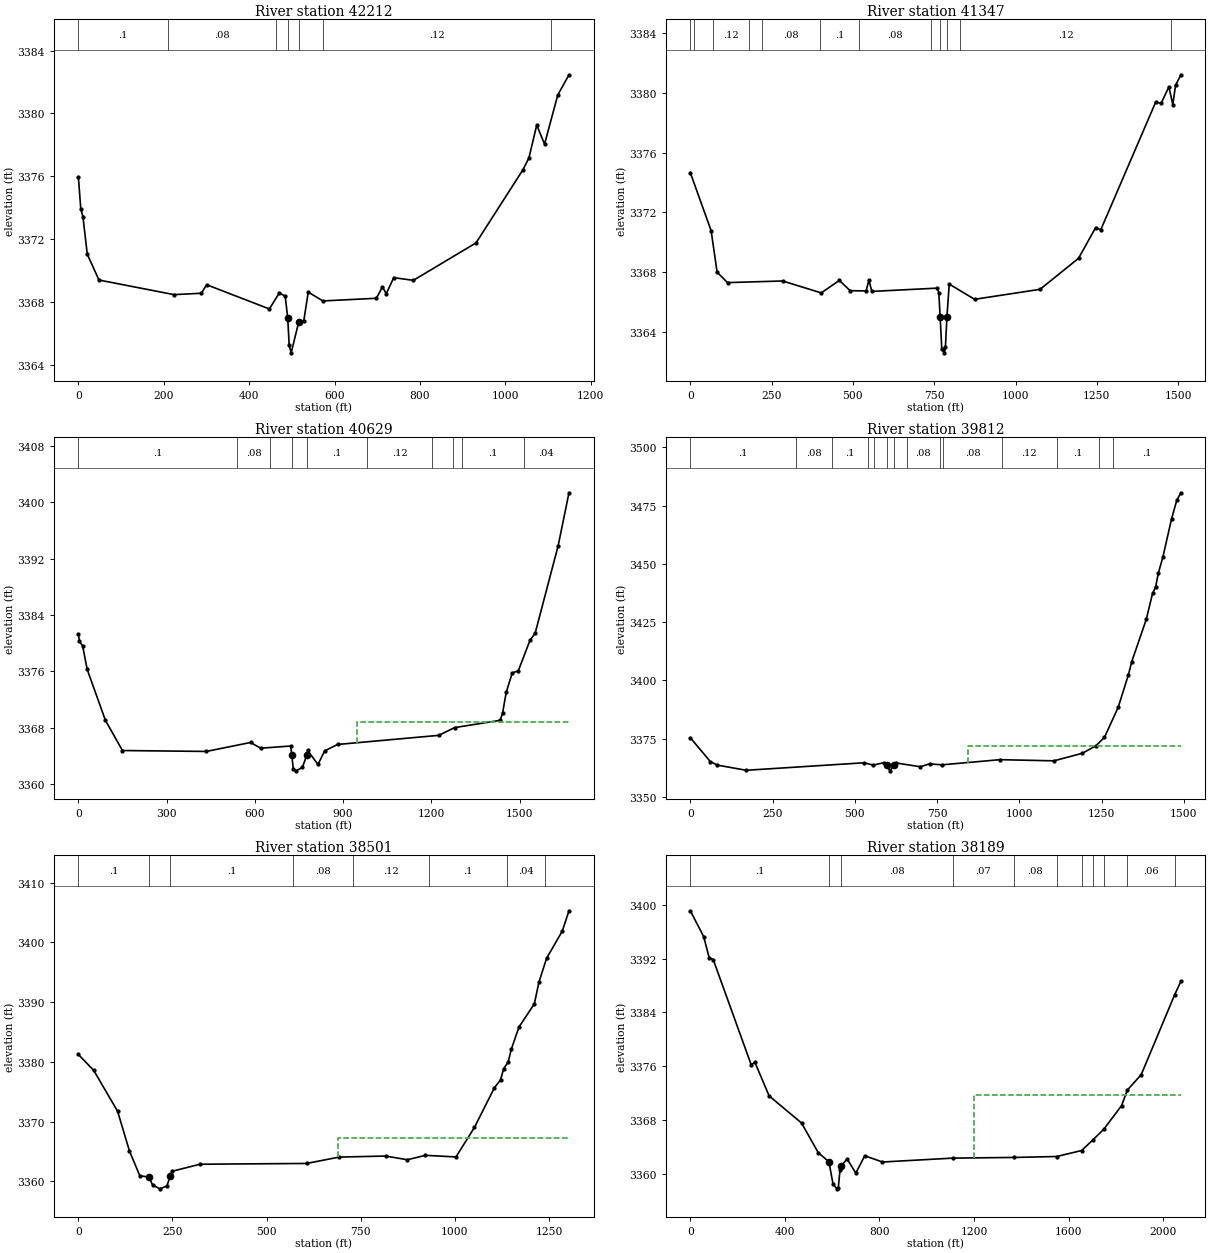
Type RM Length L Ch R = 1 ,42212   ,857.4,865,819.8
XS GIS Cut Line= 4
2183409.92904343440204.7865043842183136.35684109 440553.82690048
2183032.58807468440729.9193525652182787.31644499441167.005974703
#Sta/Elev= 30
       0 3375.95     5.6 3373.95    10.7 3373.43    20.8 3371.05    48.2 3369.41
   224.1 3368.48   288.1 3368.57   300.4 3369.11   447.4 3367.57   470.6 3368.59
   484.5 3368.38  490.343366.985   493.8 3365.25   498.4 3364.78   516.2 3366.75
   527.9 3366.81   538.4 3368.64   572.7 3368.08   697.8 3368.25   712.3 3368.97
   721.1 3368.54   738.7 3369.56   784.6 3369.39   931.4 3371.77  1041.5 3376.43
  1055.2 3377.17  1073.6 3379.26  1091.9 3378.05  1122.8 3381.17  1149.1 3382.46
#Mann= 7 ,-1,0
       0      .1       0     210     .08       0  463.48     .07       0
  490.34    .045       0   516.2     .07       0  573.48     .12       0
 1107.87      .1       0
Bank Sta=490.34,516.2
XS Rating Curve= 0 ,0
Exp/Cntr(USF)=0,0
Exp/Cntr=0.3,0.1

Type RM Length L Ch R = 1 ,41347   ,704,718.1,632.9
XS GIS Cut Line= 4
2183010.57651817439821.1565194852182661.53612207440450.058134073
2182466.57662155440799.0985301692182422.55350853441185.873023141
#Sta/Elev= 30
       0 3374.67    64.1 3370.77    82.4 3367.99   114.4 3367.29   283.7  3367.4
   402.6  3366.6   458.3 3367.44   491.3 3366.75   540.7 3366.73     549 3367.47
   558.1  3366.7   759.5 3366.92   764.1  3366.6  768.093365.009   773.2 3362.84
   781.4 3362.58   784.3 3362.94  789.08 3365.01   796.1 3367.19     874 3366.17
  1075.3 3366.84  1193.6 3368.92    1246 3370.97  1262.1 3370.84  1431.1 3379.41
  1447.3 3379.31  1471.4 3380.42  1483.5 3379.23  1491.8 3380.52  1508.3 3381.23
#Mann= 12 ,-1,0
       0     .12       0      10      .1       0      70     .12       0
     180      .1       0     220     .08       0     400      .1       0
     520     .08       0  739.27      .1       0  768.09    .045       0
  789.08      .1       0  829.27     .12       0 1479.07      .1       0
Bank Sta=768.09,789.08
XS Rating Curve= 0 ,0
Exp/Cntr(USF)=0,0
Exp/Cntr=0.3,0.1

Type RM Length L Ch R = 1 ,40629   ,802.6,817.6,775.4
XS GIS Cut Line= 4
2182556.92623211439633.072664873 2182168.7153589440206.762066383
2181922.84847254 440733.003472282181832.26593546441116.900891335
#Sta/Elev= 30
       0 3381.24     3.5 3380.29    14.6 3379.58    29.9 3376.28    91.9 3369.06
   149.9 3364.78   434.8 3364.65   585.4 3365.92   619.9 3365.11   721.9 3365.42
  725.523364.156   730.7 3362.12   739.5  3361.9   761.6 3362.38   776.2 3364.09
   779.2 3364.79   814.6  3362.8   837.5 3364.74   881.5 3365.64  1225.2 3366.93
  1279.2 3368.03    1434 3369.06  1442.2 3370.08  1454.6 3373.03  1475.1 3375.78
  1495.7 3376.08  1535.3 3380.38  1553.2 3381.44  1631.3 3393.83    1668 3401.32
#Mann= 10 ,-1,0
       0      .1       0     540     .08       0     650      .1       0
  725.52    .045       0   776.2      .1       0   982.7     .12       0
  1202.7      .1       0  1272.7     .12       0 1303.54      .1       0
 1513.54     .04       0
#XS Ineff= 2 , 0
                          946.53         3368.86
Permanent Ineff=
       F       F
Bank Sta=725.52,776.2
XS Rating Curve= 0 ,0
Exp/Cntr(USF)=0,0
Exp/Cntr=0.3,0.1

Type RM Length L Ch R = 1 ,39812   ,1298.7,1310.5,1270.7
XS GIS Cut Line= 4
2182086.75973012439499.3555863252181823.63902717439991.089359048
2181551.89141593440452.6289527452181293.08416713440754.570743013
#Sta/Elev= 30
       0 3375.41      61 3365.17    81.8 3363.67   169.9 3361.44   528.3 3364.66
   555.9 3363.67   588.1 3364.69   597.3 3363.69   606.5  3361.2   618.53363.519
     626 3364.56   699.4 3362.95   727.2 3364.21   764.4 3363.77   940.8 3365.99
  1105.2  3365.5  1191.2 3368.73  1232.5 3371.93  1258.8 3375.59  1300.6 3388.53
  1331.1 3402.24  1341.6 3408.04  1385.7 3426.16  1404.9 3437.35    1414 3439.94
  1422.6 3446.14  1436.5 3453.08  1462.8 3469.45  1478.6 3477.35    1491 3480.54
#Mann= 14 ,-1,0
       0      .1       0     320     .08       0     430      .1       0
     540     .08       0   557.7      .1       0   597.3    .045       0
   618.5      .1       0   657.7     .08       0   757.7      .1       0
   767.7     .08       0   947.7     .12       0  1113.3      .1       0
  1243.3     .04       0  1283.3      .1       0
#XS Ineff= 2 , 0
                          843.12         3371.67
Permanent Ineff=
       F       F
Bank Sta=597.3,618.5
XS Rating Curve= 0 ,0
Exp/Cntr(USF)=0,0
Exp/Cntr=0.3,0.1

Type RM Length L Ch R = 1 ,38501   ,303.7,311.7,315.5
XS GIS Cut Line= 4
2181569.14523251439335.4443287512181452.68197055439430.340319978
2180982.51546856440137.7468000362181042.90382662440435.375136158
#Sta/Elev= 30
       0 3381.24    40.7 3378.58   104.1 3371.75   135.7 3365.08   163.2 3360.94
   187.3 3360.72   196.9 3359.43   216.1 3358.75   235.3 3359.22  243.433360.854
   249.7  3361.7   322.9 3362.87   606.4    3363   693.1 3364.07   816.4 3364.24
   873.8 3363.62   922.1 3364.36  1003.1 3364.09  1052.1 3369.03  1105.2 3375.67
  1121.5    3377  1129.7 3378.85  1141.9    3380  1149.9 3382.08  1170.5 3385.84
  1211.3 3389.72  1223.5 3393.35  1243.9 3397.36  1285.6  3401.9  1303.3  3405.3
#Mann= 8 ,-1,0
       0      .1       0   187.3    .045       0  243.43      .1       0
  570.23     .08       0  730.23     .12       0  930.23      .1       0
 1139.63     .04       0 1239.63      .1       0
#XS Ineff= 2 , 0
                          689.99         3367.27
Permanent Ineff=
       F       F
Bank Sta=187.3,243.43
XS Rating Curve= 0 ,0
Exp/Cntr(USF)=0,0
Exp/Cntr=0.3,0.1

Type RM Length L Ch R = 1 ,38189   ,496,488,475.5
XS GIS Cut Line= 4
2181764.84328386439061.7627475792181416.74273032439038.221191951
2180727.35513472439815.7039966472180795.22819121440498.714844343
#Sta/Elev= 30
       0 3399.13    56.8 3395.28      80 3392.11    96.9 3391.88   257.3 3376.24
   273.3 3376.58   333.4 3371.59   470.4 3367.56   541.2 3363.14   586.13361.802
   603.6 3358.46   620.1 3357.77   625.5 3357.83   633.1 3360.59   639.13361.225
   663.1 3362.21   699.9 3360.12   737.8 3362.69   812.6 3361.76  1109.4 3362.34
  1368.7 3362.44  1549.4 3362.58  1654.8 3363.47  1700.9 3365.01  1748.4 3366.63
  1823.6 3370.15  1848.4 3372.48  1906.5 3374.74  2048.2 3386.65  2074.4 3388.64
#Mann= 11 ,-1,0
       0      .1       0   586.1    .045       0   639.1     .08       0
  1109.4     .07       0  1368.7     .08       0  1549.4     .12       0
  1654.8      .1       0  1700.9     .12       0  1748.4      .1       0
  1848.4     .06       0  2048.2      .1       0
#XS Ineff= 2 , 0
                            1200         3371.73
Permanent Ineff=
       F       F
Bank Sta=586.1,639.1
XS Rating Curve= 0 ,0
Exp/Cntr(USF)=0,0
Exp/Cntr=0.3,0.1