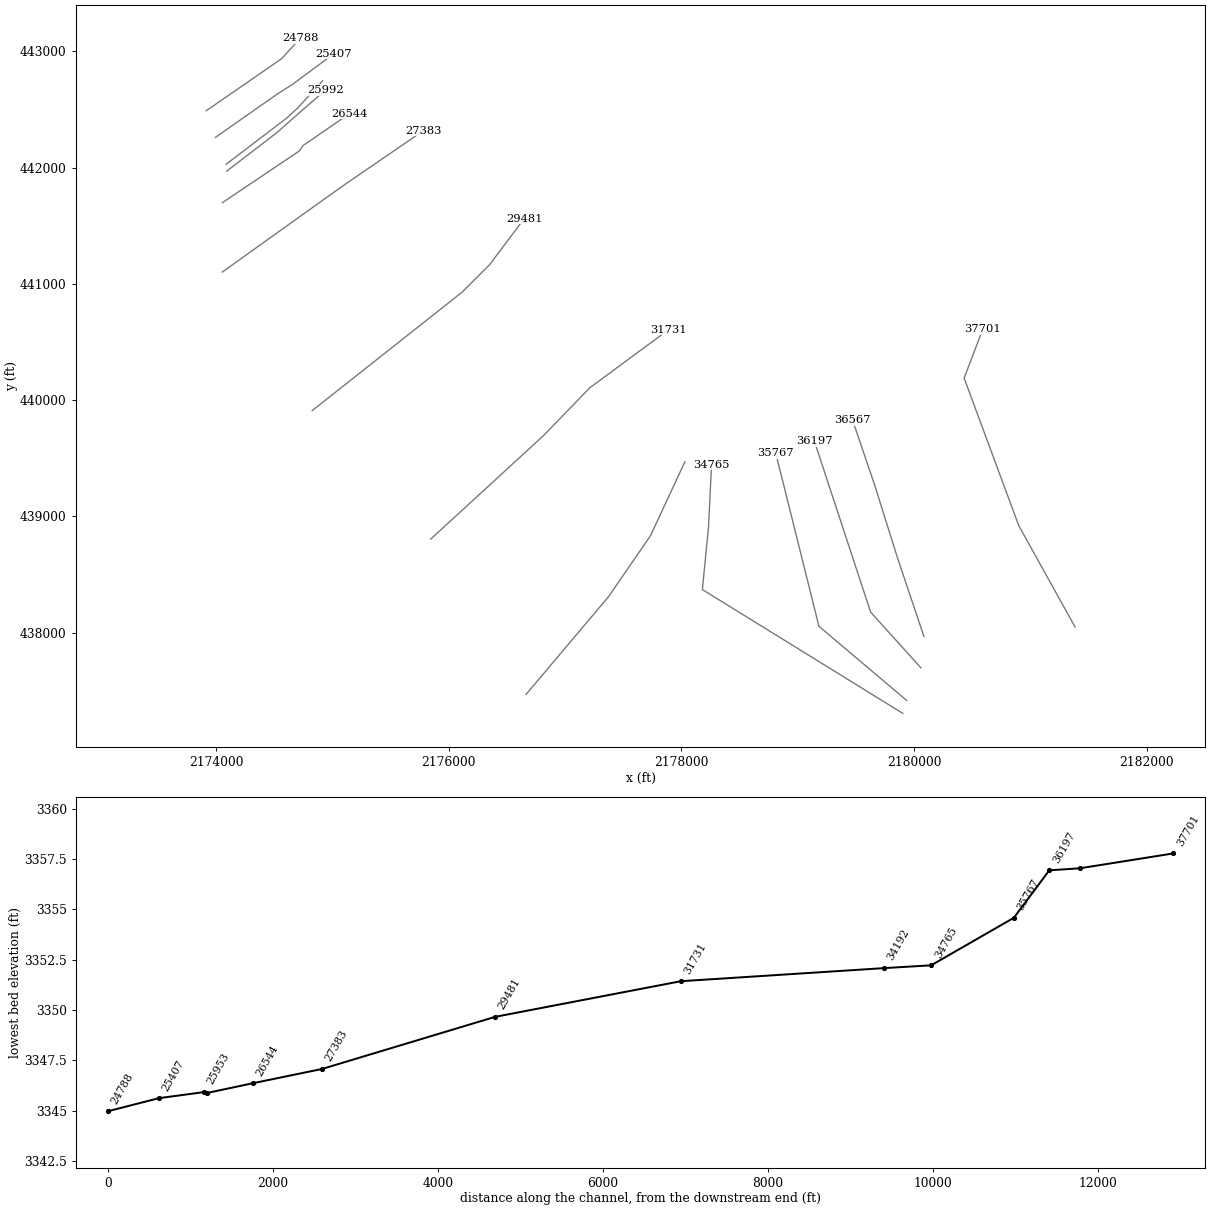
HEC-RAS study SFCRANBRYRV.prj: SFCRANBRYRV

--- SFCRANBRYRV.g01 (geometry) --- (continued)

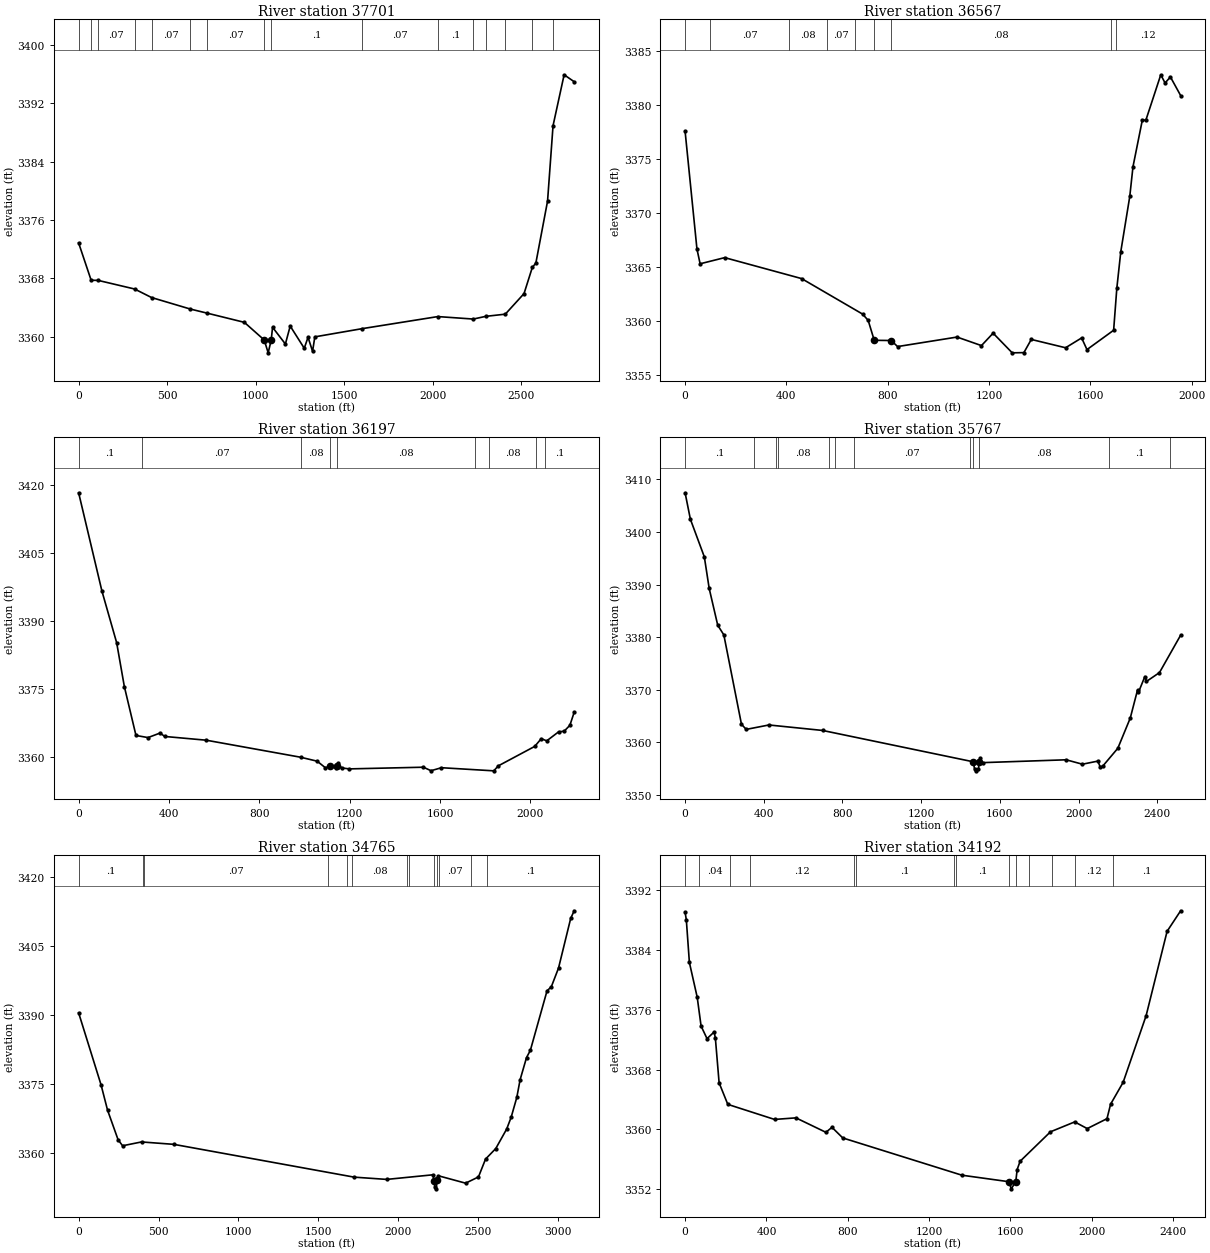
Type RM Length L Ch R = 1 ,37701   ,1100.4,1134.9,1119.8
XS GIS Cut Line= 4
2181382.49514876438048.8101850682180897.89721376438922.151518473
2180429.27503486440189.5615023162180589.03259585 440610.25641292
#Sta/Elev= 30
       0 3372.84    70.7 3367.73   110.2 3367.71   316.1 3366.53   412.1 3365.36
   631.3 3363.78   727.8 3363.21   936.4 3361.96  1048.8 3359.54    1071 3357.78
 1088.08 3359.52  1095.8 3361.28  1168.3 3358.99  1195.5 3361.45  1274.9 3358.41
  1296.3 3359.91  1321.9 3357.99  1334.7 3359.97  1603.3  3361.1  2029.8 3362.75
  2230.2 3362.41  2300.2 3362.78  2410.9 3363.08  2516.8  3365.9  2563.6 3369.49
  2583.6 3370.08  2649.7 3378.58  2680.7 3388.91  2743.3 3395.89  2800.1 3394.94
#Mann= 16 ,-1,0
       0      .1       0    70.7     .08       0   110.2     .07       0
   316.1     .08       0   412.1     .07       0   631.3      .1       0
   727.8     .07       0  1048.8    .045       0 1088.08      .1       0
  1603.3     .07       0  2029.8      .1       0  2230.2     .12       0
  2300.2     .08       0  2410.9     .12       0  2563.6     .04       0
  2680.7      .1       0
Bank Sta=1048.8,1088.08
XS Rating Curve= 0 ,0
Exp/Cntr(USF)=0,0
Exp/Cntr=0.3,0.1

Type RM Length L Ch R = 1 ,36567   ,369.8,369.6,369.4
XS GIS Cut Line= 4
2180083.13365272437968.9314045742179859.47306733438634.587908693
2179662.43874211439262.9676485822179470.72966893439827.444364075
#Sta/Elev= 30
       0 3377.54    46.8 3366.65    59.3 3365.28   156.4 3365.85   460.2 3363.91
   700.6 3360.63   722.9 3360.05   746.9  3358.2   813.9 3358.18   839.1 3357.62
  1073.9  3358.5  1170.3 3357.71  1216.4 3358.86  1291.8 3357.04  1337.9 3357.06
  1367.1 3358.28  1502.5 3357.51  1565.9 3358.42    1587 3357.34  1692.3 3359.13
  1704.9 3363.02  1720.6 3366.41    1756 3371.51  1768.7 3374.26  1805.8  3378.6
  1819.3 3378.55  1878.5 3382.77  1895.4 3382.01  1916.5 3382.57  1956.9 3380.85
#Mann= 9 ,-1,0
       0      .1       0     100     .07       0     410     .08       0
     560     .07       0     670     .08       0   746.9    .045       0
   813.9     .08       0 1680.77      .1       0 1700.77     .12       0
Bank Sta=746.9,813.9
XS Rating Curve= 0 ,0
Exp/Cntr(USF)=0,0
Exp/Cntr=0.3,0.1

Type RM Length L Ch R = 1 ,36197   ,431.3,429.9,426.9
XS GIS Cut Line= 3
2180058.13804698437697.4818754872179625.74212729438177.048259148
2179142.24487163439647.194386112
#Sta/Elev= 30
       0 3418.31   103.1 3396.62   168.3 3385.22   202.3 3375.55   253.8 3364.75
   307.1 3364.28   360.9 3365.29   380.7 3364.53   565.1  3363.7   982.9 3359.94
  1055.8 3359.07  1092.2 3357.62  1111.7 3357.96  1138.2 3357.51 1143.59 3358.09
  1147.7 3358.62  1163.8 3357.59  1197.5 3357.37  1525.9 3357.74  1559.6 3356.97
  1605.9 3357.63  1837.5 3356.94  1857.5 3358.04  2018.6 3362.33  2047.6 3364.04
  2071.9 3363.56  2124.2 3365.54    2149 3365.69  2174.4    3367  2193.3 3369.86
#Mann= 9 ,-1,0
       0      .1       0     280     .07       0  985.72     .08       0
  1111.7    .045       0 1143.59     .08       0 1755.72     .07       0
 1815.72     .08       0 2025.72     .12       0 2065.72      .1       0
Bank Sta=1111.7,1143.59
XS Rating Curve= 0 ,0
Exp/Cntr(USF)=0,0
Exp/Cntr=0.3,0.1

Type RM Length L Ch R = 1 ,35767   ,1005.9,1001.7,990
XS GIS Cut Line= 4
2179934.94700973437418.0636664982179181.13743696438055.320310366
2178896.19414404439199.722062709 2178810.7271361439541.590094455
#Sta/Elev= 30
       0 3407.45    26.9 3402.42    97.8 3395.26   122.5 3389.25   165.9 3382.26
   196.9 3380.43   286.5 3363.44   310.7 3362.46   426.1  3363.3   698.8 3362.26
  1464.7  3356.3  1471.3 3354.91  1479.5 3354.58  1491.1 3354.91 1494.56 3356.22
  1500.1 3356.98  1512.5 3356.14  1937.1 3356.68  2019.5 3355.84  2097.8 3356.43
  2110.2 3355.31  2122.6 3355.46  2199.5 3358.87  2262.8 3364.62  2299.6 3369.94
    2304 3369.48    2337 3372.51  2345.2 3371.58  2411.2 3373.26  2518.8 3380.37
#Mann= 12 ,-1,0
       0      .1       0     350     .08       0     460     .07       0
     470     .08       0     730     .07       0     760     .08       0
     860     .07       0 1447.08     .08       0  1464.7    .045       0
 1494.56     .08       0 2157.08      .1       0 2466.42     .08       0
Bank Sta=1464.7,1494.56
XS Rating Curve= 0 ,0
Exp/Cntr(USF)=0,0
Exp/Cntr=0.3,0.1

Type RM Length L Ch R = 1 ,34765   ,585,573.8,559.9
XS GIS Cut Line= 4
 2179902.0750836437306.2991176592178179.58615442 438371.34952425
2178232.18123623438903.8747275452178258.47877713439442.974316067
#Sta/Elev= 30
       0 3390.46   140.1 3374.84   180.9 3369.32   246.8 3362.89     275 3361.58
   393.4 3362.41   594.8 3361.89  1723.8 3354.76  1927.3 3354.27  2215.9 3355.27
    2224 3353.95    2228 3352.55    2236 3352.22  2244.1 3354.09  2248.1 3355.08
  2420.9 3353.45  2501.3 3354.81  2545.5 3358.68  2609.6 3360.98  2677.7 3365.21
  2705.8 3367.77    2741 3372.07  2761.8 3375.93  2801.9 3380.74  2825.9 3382.32
    2930 3395.22  2957.4 3396.16  3002.1 3400.19  3078.2 3410.98    3100 3412.64
#Mann= 13 ,-1,0
       0      .1       0     400     .08       0     410     .07       0
    1560     .08       0    1680      .1       0    1710     .08       0
 2055.17     .07       0 2065.17      .1       0    2224    .045       0
  2244.1      .1       0 2255.17     .07       0 2455.17     .12       0
 2555.17      .1       0
Bank Sta=2224,2244.1
XS Rating Curve= 0 ,0
Exp/Cntr(USF)=0,0
Exp/Cntr=0.3,0.1

Type RM Length L Ch R = 1 ,34192   ,2286.8,2460.3,2335.3
XS GIS Cut Line= 4
2176664.31303593437469.0743950162177375.16700876 438312.03397342
2177733.73936674 438834.165652582178029.40429349439469.530707944
#Sta/Elev= 30
       0 3388.96       6 3387.99    21.1 3382.28    59.6 3377.64    78.6  3373.8
   107.8 3372.12   142.5    3373   148.7 3372.24   167.3 3366.22     210 3363.35
     440 3361.34     545 3361.55   692.6 3359.62   722.2 3360.29   775.4 3358.87
  1361.2  3353.9  1592.53353.031  1603.9 3352.08 1626.09 3353.03    1633 3354.66
  1647.5 3355.76  1796.8 3359.69  1915.9 3361.01  1977.6 3360.12  2074.7 3361.44
  2092.4 3363.37  2154.1 3366.29  2267.1 3375.18  2370.3 3386.44  2436.9 3389.18
#Mann= 14 ,-1,0
       0      .1       0      70     .04       0     220      .1       0
     320     .12       0     830     .08       0     840      .1       0
 1322.68     .08       0 1332.68      .1       0  1592.5    .045       0
 1626.09      .1       0 1692.68     .12       0 1806.08      .1       0
 1916.08     .12       0 2106.08      .1       0
Bank Sta=1592.5,1626.09
XS Rating Curve= 0 ,0
Exp/Cntr(USF)=0,0
Exp/Cntr=0.3,0.1

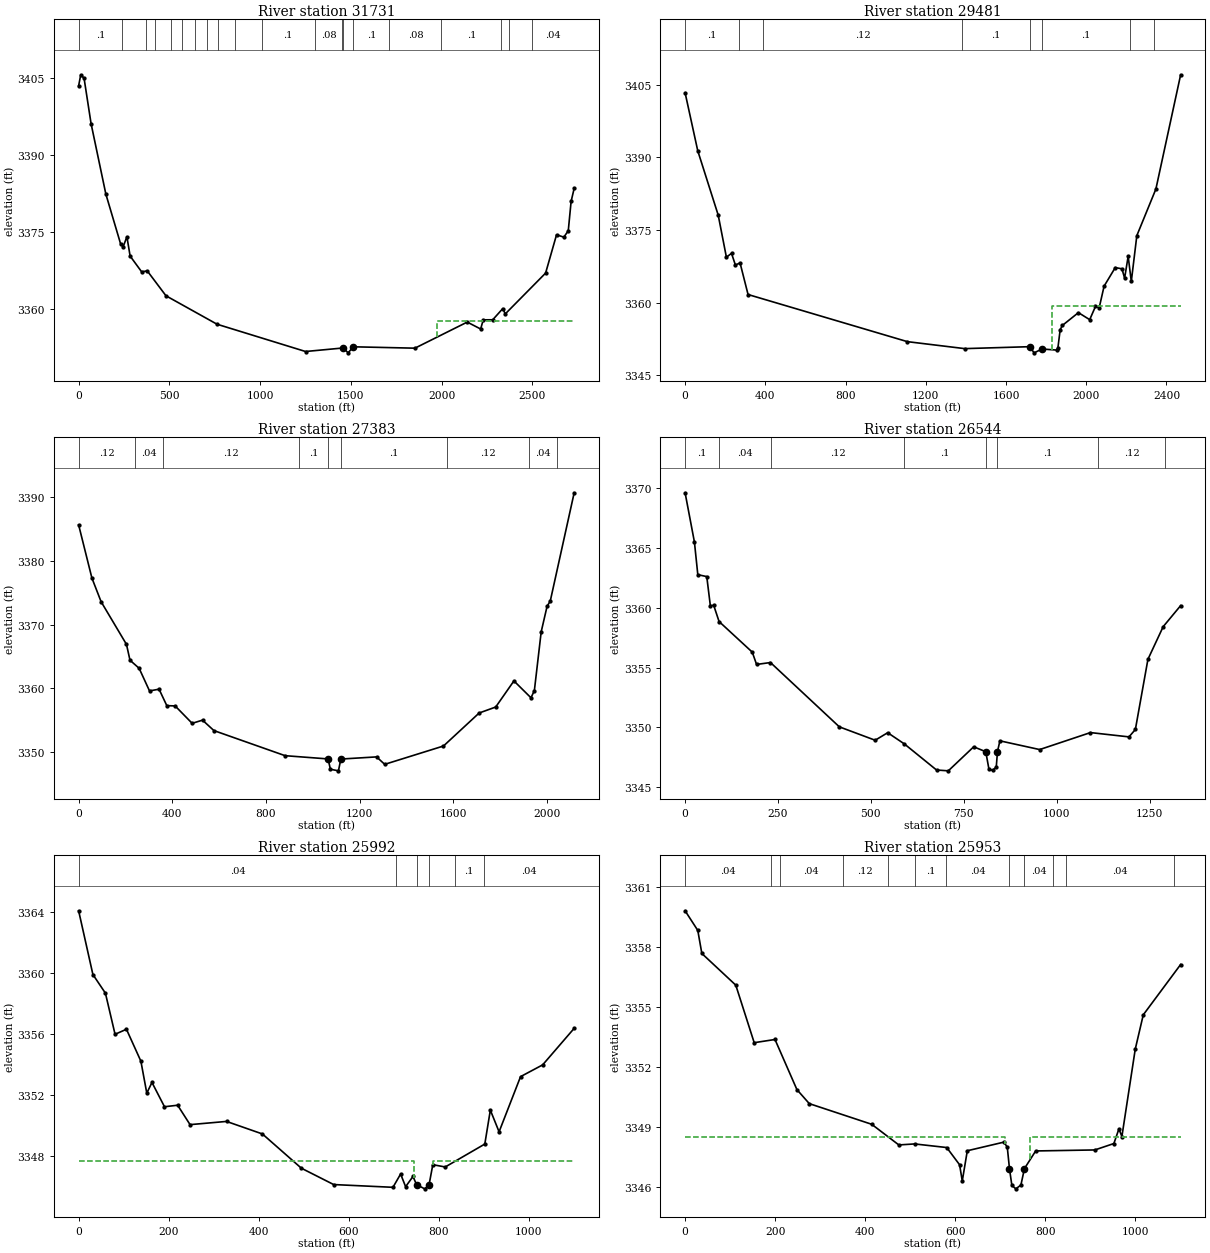
Type RM Length L Ch R = 1 ,31731   ,2140.6,2250.1,2050.6
XS GIS Cut Line= 4
2175845.67939923438805.2589491572176812.11402744 439692.80095465
2177213.15152622 440106.987223882177890.31320448440606.640501046
#Sta/Elev= 30
       0 3403.54    11.7 3405.68      30    3405    68.6 3396.14     150  3382.4
     231 3372.72   245.2 3372.12     266 3374.08   283.7 3370.31   347.1 3367.24
   378.1 3367.42   481.3 3362.56   762.7 3357.01  1250.2 3351.69  1457.4 3352.38
    1485 3351.43  1513.1 3352.61  1852.8 3352.34    2141 3357.43    2215 3356.08
  2229.2 3357.87  2281.4 3357.88    2337 3360.07  2350.5 3359.02  2572.8 3366.99
  2633.1 3374.47  2673.3    3374  2697.7 3375.25  2713.3 3380.97  2730.2 3383.52
#Mann= 20 ,-1,0
       0      .1       0     240     .04       0     370      .1       0
     420     .12       0     510      .1       0     570     .12       0
     640      .1       0     710     .08       0     770      .1       0
     860     .08       0    1010      .1       0    1300     .08       0
 1452.15      .1       0  1457.4    .045       0  1513.1      .1       0
 1712.15     .08       0 1998.67      .1       0 2328.67     .04       0
 2368.67      .1       0 2498.67     .04       0
#XS Ineff= 2 , 0
                         1972.35         3357.73
Permanent Ineff=
       F       F
Bank Sta=1457.4,1513.1
XS Rating Curve= 0 ,0
Exp/Cntr(USF)=0,0
Exp/Cntr=0.3,0.1

Type RM Length L Ch R = 1 ,29481   ,1961.5,2097.9,1928
XS GIS Cut Line= 4
2174826.64968922439909.755667104 2176115.2291935440928.785377114
2176351.90706163441165.4632452452176647.75439679441559.926358797
#Sta/Elev= 30
       0 3403.36    63.1 3391.38   165.1 3378.09   205.9 3369.41   231.4  3370.2
   250.6 3367.81   274.1 3368.21   313.9  3361.7  1108.2 3351.97  1394.1 3350.53
  1717.3 3350.93  1740.3 3349.66  1779.5 3350.45  1853.1 3350.23  1858.7 3350.69
    1870 3354.44    1881 3355.32  1960.9 3357.96  2017.2 3356.51  2046.1 3359.25
  2064.6 3358.98    2089 3363.43  2144.6 3367.26    2178 3367.01  2191.3 3365.08
    2209  3369.6  2224.6 3364.39  2252.2 3373.86  2347.2 3383.48  2470.6 3407.07
#Mann= 8 ,-1,0
       0      .1       0     270     .04       0     390     .12       0
    1380      .1       0  1717.3    .045       0  1779.5      .1       0
 2217.53     .04       0 2337.53      .1       0
#XS Ineff= 2 , 0
                         1827.96         3359.43
Permanent Ineff=
       F       F
Bank Sta=1717.3,1779.5
XS Rating Curve= 0 ,0
Exp/Cntr(USF)=0,0
Exp/Cntr=0.3,0.1

Type RM Length L Ch R = 1 ,27383   ,779.5,839.4,807.6
XS GIS Cut Line= 4
2174054.13312764 441101.284096672174864.10396186441681.204043059
  2175113.325757441858.5349357562175784.30751315442318.636711404
#Sta/Elev= 30
       0 3385.69    56.6 3377.35      96 3373.62   204.2 3366.93   219.3 3364.44
   258.3 3363.17   302.6 3359.62   343.4 3359.89   376.4 3357.31   412.1 3357.26
   484.6 3354.53   528.9 3355.03   577.6 3353.39   881.5 3349.45    1065 3348.94
  1074.8 3347.32  1109.2 3347.07  1119.5 3348.92  1272.1 3349.26  1306.7 3348.09
  1557.7 3350.97  1709.9 3356.15  1780.6 3357.09  1858.4 3361.19  1931.2 3358.54
  1945.7 3359.68  1974.8  3368.9  1999.9  3372.9  2013.6 3373.74  2115.6 3390.73
#Mann= 9 ,-1,0
       0     .12       0     240     .04       0     360     .12       0
     940      .1       0    1065    .045       0  1119.5      .1       0
 1572.04     .12       0 1922.04     .04       0 2042.04      .1       0
Bank Sta=1065,1119.5
XS Rating Curve= 0 ,0
Exp/Cntr(USF)=0,0
Exp/Cntr=0.3,0.1

Type RM Length L Ch R = 1 ,26544   ,304.5,551.7,518.8
XS GIS Cut Line= 4
2174055.83462164  441698.68242672174713.73803418442141.105279039
2174748.12322996442189.244553128 2175144.6991546442462.033772964
#Sta/Elev= 30
       0 3369.62    25.1  3365.5    34.2 3362.77    58.3 3362.61    67.9 3360.18
      77  3360.2    91.4 3358.85   180.7 3356.29   192.3 3355.26   229.7 3355.42
     415 3350.04   511.4 3348.92   545.1 3349.55     590 3348.61   676.5 3346.43
   708.2 3346.36   776.5 3348.37     809 3347.96   817.5  3346.5   827.3  3346.4
   837.2 3346.67   840.5 3347.97     847 3348.87     954 3348.14  1090.7 3349.56
  1194.3  3349.2  1211.5 3349.82  1245.3 3355.69  1286.3 3358.42  1333.3 3360.18
#Mann= 8 ,-1,0
       0      .1       0      90     .04       0     230     .12       0
     590      .1       0     809    .045       0   840.5      .1       0
 1111.99     .12       0 1291.99      .1       0
Bank Sta=809,840.5
XS Rating Curve= 0 ,0
Exp/Cntr(USF)=0,0
Exp/Cntr=0.5,0.3

Type RM Length L Ch R = 1 ,25992   ,179.2,39.3,43.9
XS GIS Cut Line= 4
2174092.01879745441968.8974302592174524.49643107442301.478821752
2174744.99911188442496.3983185982174942.35510244442666.952878338
#Sta/Elev= 30
       0 3364.07    31.7  3359.9    59.5 3358.68    80.9 3355.99   106.2 3356.32
   138.3 3354.23   151.4 3352.14   162.9 3352.84   190.7 3351.25   219.9 3351.35
   247.5 3350.08   328.5 3350.29   408.2 3349.47   494.7 3347.23   566.5 3346.16
   698.2 3345.98   715.2 3346.85   726.3 3346.02   742.7 3346.69   750.5 3346.16
   768.6 3345.88  778.29 3346.13   786.7 3347.46   814.3 3347.31   902.2 3348.81
   914.5 3351.03   933.9 3349.61   981.6 3353.22  1030.7 3353.99  1100.7 3356.38
#Mann= 6 ,-1,0
       0     .04       0  705.57      .1       0   750.5    .045       0
  778.29     .04       0  835.57      .1       0  899.87     .04       0
#XS Ineff= 2 , 0
          744.61 3347.72  788.12         3347.73
Permanent Ineff=
       F       F
Bank Sta=750.5,778.29
XS Rating Curve= 0 ,0
Exp/Cntr(USF)=0,0
Exp/Cntr=0.5,0.3

Type RM Length L Ch R = 1 ,25953   ,528.1,545.6,507.3
XS GIS Cut Line= 4
2174086.62748019442028.0965096162174610.60763512442427.742390492
2174704.35173063442514.5790263362174916.18049383442746.362673023
#Sta/Elev= 30
       0 3359.79    28.2 3358.81    37.2 3357.66   112.6 3356.08   153.5 3353.21
   199.7 3353.37   248.4 3350.87   275.9 3350.17   414.5 3349.14   474.8 3348.11
     510 3348.16   581.2 3347.98   609.8 3347.12   615.7 3346.31   626.9 3347.82
   708.2 3348.25   715.7    3348   720.6 3346.92   725.9 3346.09   734.7 3345.92
     746 3346.11   753.8 3346.93   778.8 3347.81   910.2 3347.86   952.5 3348.18
   963.7 3348.91   970.3 3348.53    1000 3352.89  1017.8  3354.6  1100.8 3357.11
#Mann= 12 ,-1,0
       0     .04       0     190     .12       0     210     .04       0
     350     .12       0     450     .04       0     510      .1       0
     580     .04       0   720.6    .045       0   753.8     .04       0
  816.78     .06       0  846.78     .04       0 1086.78     .12       0
#XS Ineff= 2 , 0
          711.55 3348.53     767         3348.53
Permanent Ineff=
       F       F
Bank Sta=720.6,753.8
XS Rating Curve= 0 ,0
Exp/Cntr(USF)=0,0
Exp/Cntr=0.5,0.3

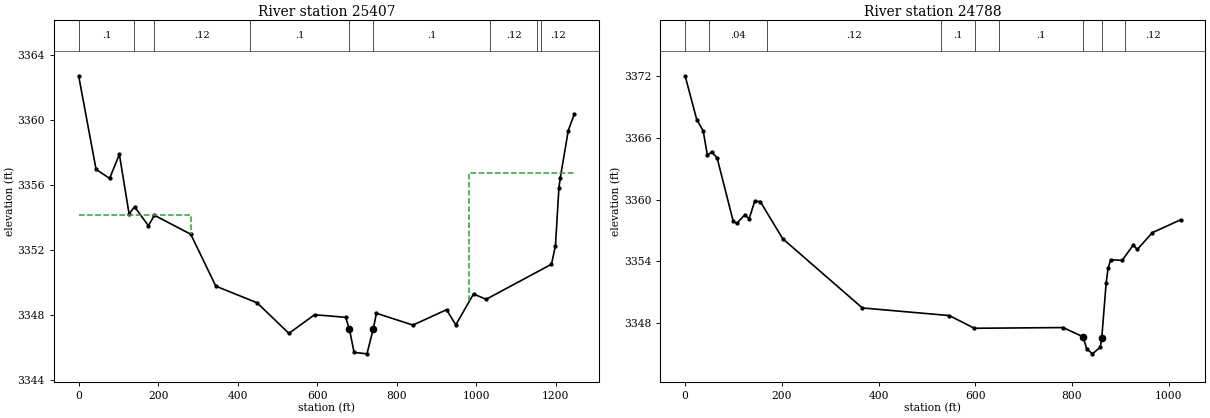
Type RM Length L Ch R = 1 ,25407   ,605.2,619.2,540.3
XS GIS Cut Line= 4
2173996.23361562442260.307291069 2174525.7656306442631.667405467
2174658.72172094442716.4842217192175014.03541064442980.104056014
#Sta/Elev= 30
       0 3362.75    43.9 3356.98      78 3356.43   102.5 3357.91   126.9 3354.25
   140.8 3354.68   175.7 3353.51   190.5 3354.16     282 3352.99   345.2 3349.79
   449.4 3348.76     529 3346.88   593.7 3348.03   671.9 3347.87   681.5 3347.12
   693.1 3345.71   725.5 3345.62   741.4 3347.16   749.3 3348.12   841.2 3347.39
   925.8 3348.34     949  3347.4   993.6 3349.31  1025.4 3348.98  1189.8 3351.14
  1199.8 3352.28  1208.4 3355.81    1212 3356.47    1232 3359.37  1246.9 3360.37
#Mann= 9 ,-1,0
       0      .1       0     140     .04       0     190     .12       0
     430      .1       0   681.5    .045       0   741.4      .1       0
 1034.48     .12       0 1154.48      .1       0 1164.48     .12       0
#XS Ineff= 2 , 0
          281.85 3354.15   982.8         3356.74
Permanent Ineff=
       F       F
Bank Sta=681.5,741.4
XS Rating Curve= 0 ,0
Exp/Cntr(USF)=0,0
Exp/Cntr=0.3,0.1

Type RM Length L Ch R = 1 ,24788   ,237.6,227,218.7
XS GIS Cut Line= 4
2173916.45145408442488.7618868162174564.82950261442936.806008037
2174639.27792154443019.3760726732174724.55520141443111.421390628
#Sta/Elev= 30
       0 3372.06      24  3367.8    37.5 3366.68    46.1  3364.3    54.7 3364.64
    66.2 3364.06    99.2 3357.94   106.5 3357.67   123.7 3358.52   132.4 3358.13
   143.9 3359.82   155.4 3359.81   201.8 3356.19   366.6 3349.44   546.4  3348.7
   598.2 3347.46   781.7 3347.53     823 3346.63   830.4 3345.47   842.5 3344.97
   858.6 3345.62   861.6 3346.48   870.8 3351.89   874.8 3353.33   880.2 3354.13
     904 3354.08   926.7 3355.57   935.2 3355.14   966.3 3356.78  1024.8 3358.03
#Mann= 9 ,-1,0
       0      .1       0      50     .04       0     170     .12       0
     530      .1       0     600     .12       0     650      .1       0
     823    .045       0   861.6      .1       0   909.3     .12       0
Bank Sta=823,861.6
XS Rating Curve= 0 ,0
Exp/Cntr(USF)=0,0
Exp/Cntr=0.3,0.1