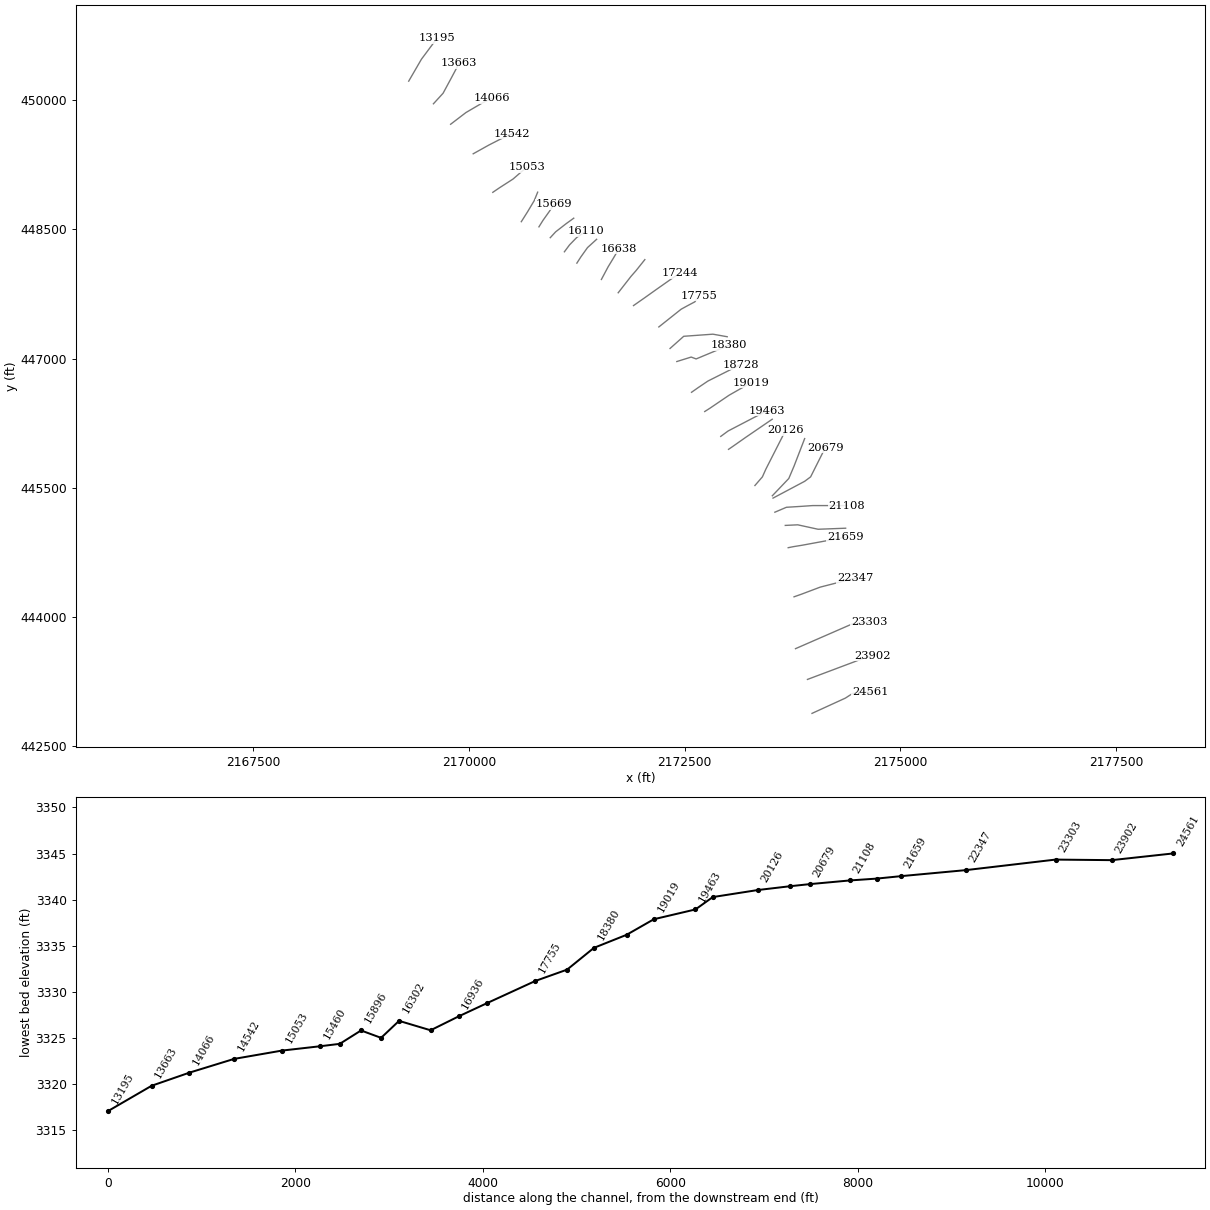
HEC-RAS study SFCRANBRYRV.prj: SFCRANBRYRV

--- SFCRANBRYRV.g01 (geometry) --- (continued)

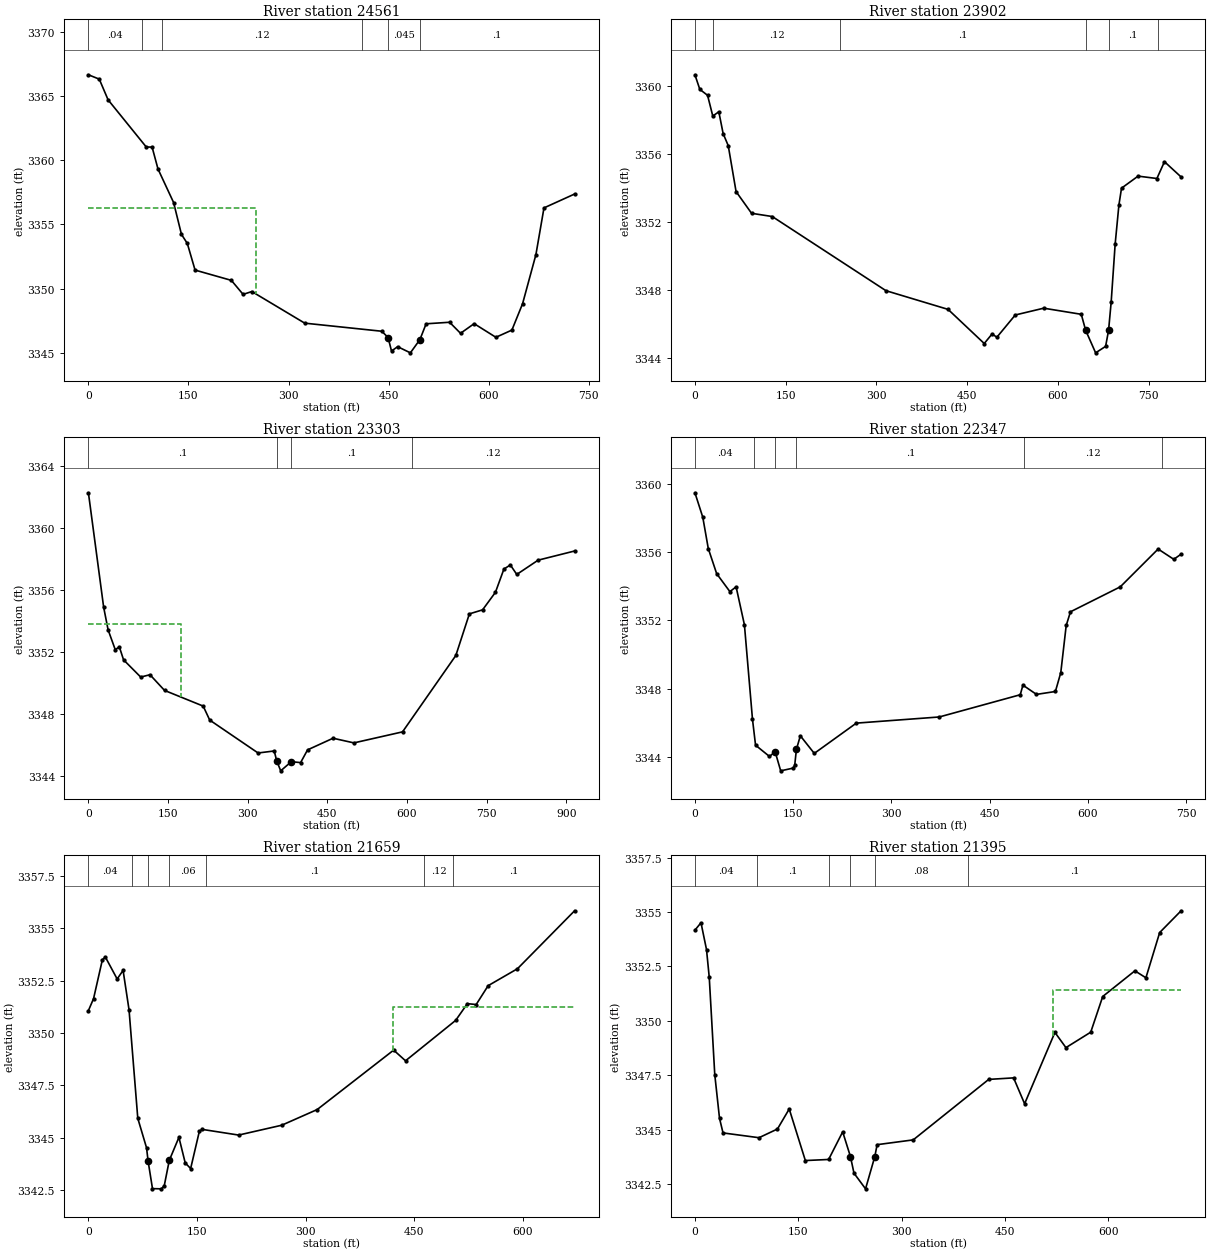
Type RM Length L Ch R = 1 ,24561   ,632.8,658.6,598.2
XS GIS Cut Line= 5
2173977.36379684442884.015310974 2174364.4955753443061.337908799
2174445.71203232443114.128605861 2174532.3429198443131.725504882
2174650.10678248443127.664682031
#Sta/Elev= 30
       0 3366.65    16.3 3366.31    29.5  3364.7    86.7 3361.03    95.5 3361.02
   104.3 3359.32   127.7 3356.71   139.5 3354.23   148.3 3353.52   159.9 3351.45
   214.3 3350.65   231.9 3349.56   245.1 3349.78   324.3 3347.32   439.9 3346.69
   449.3  3346.2   454.4 3345.15   463.6 3345.49   482.7 3345.01     497 3346.04
   506.3 3347.27   541.5 3347.39   557.9 3346.53   578.3 3347.28   610.9 3346.22
   634.9 3346.78   650.9 3348.83   670.9 3352.65     683 3356.29   728.9 3357.37
#Mann= 6 ,-1,0
       0     .04       0      80      .1       0     110     .12       0
     410      .1       0   449.3    .045       0     497      .1       0
#XS Ineff= 2 , 0
          251.92 3356.31
Permanent Ineff=
       F       F
Bank Sta=449.3,497
XS Rating Curve= 0 ,0
Exp/Cntr(USF)=0,0
Exp/Cntr=0.3,0.1

Type RM Length L Ch R = 1 ,23902   ,596.5,599.2,597.8
XS GIS Cut Line= 4
2173924.57309978443277.915127516 2174460.6017161443479.602662447
2174583.78000925443526.9789290412174678.53254244443555.404688998
#Sta/Elev= 30
       0 3360.66     8.1  3359.8    20.9 3359.45    29.5 3358.23    39.5 3358.48
    46.6  3357.2    55.1 3356.48      68 3353.78    93.6  3352.5   127.8 3352.31
   315.8 3347.94   418.4 3346.84   478.2 3344.83   491.1 3345.39   499.1  3345.2
   529.5 3346.51   576.5 3346.91   638.6 3346.55   645.8 3345.61   662.3 3344.28
   678.8 3344.66   683.7  3345.6     688 3347.27   694.6 3350.69   700.8 3352.99
   705.1 3353.98   732.5 3354.69   763.6 3354.55   776.1 3355.54   803.6 3354.64
#Mann= 6 ,-1,0
       0      .1       0      30     .12       0     240      .1       0
   645.8    .045       0   683.7      .1       0  764.69     .12       0
Bank Sta=645.8,683.7
XS Rating Curve= 0 ,0
Exp/Cntr(USF)=0,0
Exp/Cntr=0.3,0.1

Type RM Length L Ch R = 1 ,23303   ,785.1,955.8,881.2
XS GIS Cut Line= 3
2173785.86184597443634.6934702462174445.09787579443922.455229296
2174640.42706982443943.383357227
#Sta/Elev= 30
       0 3362.25    28.7 3354.88    37.1 3353.42    50.5 3352.15    58.3 3352.32
    66.2 3351.49    98.5 3350.38     116 3350.53   143.4 3349.52   216.2 3348.51
   228.5 3347.61   319.6 3345.49     350 3345.62  354.66 3344.99   362.2 3344.34
   382.2 3344.93   399.7 3344.87   412.8 3345.69   460.8 3346.44   500.1 3346.14
   591.7 3346.85   692.1 3351.77   717.6 3354.45   742.5 3354.71   766.7 3355.84
   782.7 3357.34   794.8  3357.6   806.9 3356.99   847.1 3357.91   915.8  3358.5
#Mann= 4 ,-1,0
       0      .1       0  354.66    .045       0   382.2      .1       0
     610     .12       0
#XS Ineff= 2 , 0
          173.58 3353.83
Permanent Ineff=
       F       F
Bank Sta=354.66,382.2
XS Rating Curve= 0 ,0
Exp/Cntr(USF)=0,0
Exp/Cntr=0.3,0.1

Type RM Length L Ch R = 1 ,22347   ,684.3,688.7,680.8
XS GIS Cut Line= 4
2173768.90822382 444236.269320342173856.89271893 444267.40229553
2174072.11633003444348.6187525492174478.19861512444452.846539057
#Sta/Elev= 30
       0 3359.46      12 3358.03    20.4  3356.2    33.2 3354.73    53.4 3353.68
    62.9 3353.96    75.6 3351.74    87.9 3346.22    92.6  3344.7   113.9 3344.04
   122.5 3344.32     131  3343.2     150 3343.36   152.4 3343.52     155 3344.45
     161 3345.25   182.3 3344.22   246.5 3345.99   373.2 3346.35   496.9 3347.65
     501 3348.21   521.7 3347.67   550.6 3347.84   558.8 3348.94   567.1  3351.7
   573.6  3352.5   649.7 3353.96   707.5 3356.17   731.4 3355.57   742.6 3355.87
#Mann= 6 ,-1,0
       0     .04       0      90      .1       0   122.5    .045       0
     155      .1       0  503.37     .12       0  713.37      .1       0
Bank Sta=122.5,155
XS Rating Curve= 0 ,0
Exp/Cntr(USF)=0,0
Exp/Cntr=0.3,0.1

Type RM Length L Ch R = 1 ,21659   ,270.3,263.7,255.1
XS GIS Cut Line= 4
2173701.22784297 444806.138127092173762.14018574444818.320595642
 2173862.3071494444834.5638870462174361.78836006444926.609205001
#Sta/Elev= 30
       0 3351.07     7.1 3351.64    19.3  3353.5    23.4 3353.63    39.7 3352.58
    47.9 3352.99    56.1 3351.11    68.2 3345.92    80.3 3344.51   82.42 3343.88
    88.5 3342.56   100.7 3342.55   104.7 3342.69   111.7 3343.91     125 3345.01
   133.7 3343.79   141.2 3343.52   153.3 3345.31   157.4 3345.39   207.5 3345.12
     267 3345.59     316 3346.34   421.6 3349.18     438 3348.67   507.2  3350.6
   523.4  3351.4   535.6 3351.36   552.1 3352.26   592.6 3353.07   671.5 3355.84
#Mann= 7 ,-1,0
       0     .04       0      60     .06       0   82.42    .045       0
   111.7     .06       0  162.12      .1       0  463.59     .12       0
  503.59      .1       0
#XS Ineff= 2 , 0
                          420.46         3351.23
Permanent Ineff=
       F       F
Bank Sta=82.42,111.7
XS Rating Curve= 0 ,0
Exp/Cntr(USF)=0,0
Exp/Cntr=0.3,0.1

Type RM Length L Ch R = 1 ,21395   ,275.3,287,288.7
XS GIS Cut Line= 4
2173667.38765255445064.6771819332173812.22366757445071.445220018
2174047.75139292445020.0081305732174367.20279053445032.190599126
#Sta/Elev= 30
       0 3354.17     8.8 3354.51    16.8 3353.28    20.8    3352    28.8 3347.53
    35.7 3345.52    40.8 3344.85      93 3344.63   119.8 3345.03   136.9 3345.95
   160.3 3343.58   194.1 3343.63   214.5  3344.9   225.8 3343.76   230.9    3343
   247.7 3342.28   261.1 3343.76   264.5 3344.31   316.9 3344.53   426.5 3347.31
   462.6 3347.38   478.6 3346.19   522.6 3349.47   538.6 3348.77   574.6 3349.48
     592 3351.12   638.7  3352.3   654.7 3351.98   674.7 3354.06   705.8 3355.06
#Mann= 6 ,-1,0
       0     .04       0      90      .1       0  194.99     .08       0
   225.8    .045       0   261.1     .08       0  396.07      .1       0
#XS Ineff= 2 , 0
                          520.13         3351.44
Permanent Ineff=
       F       F
Bank Sta=225.8,261.1
XS Rating Curve= 0 ,0
Exp/Cntr(USF)=0,0
Exp/Cntr=0.3,0.1

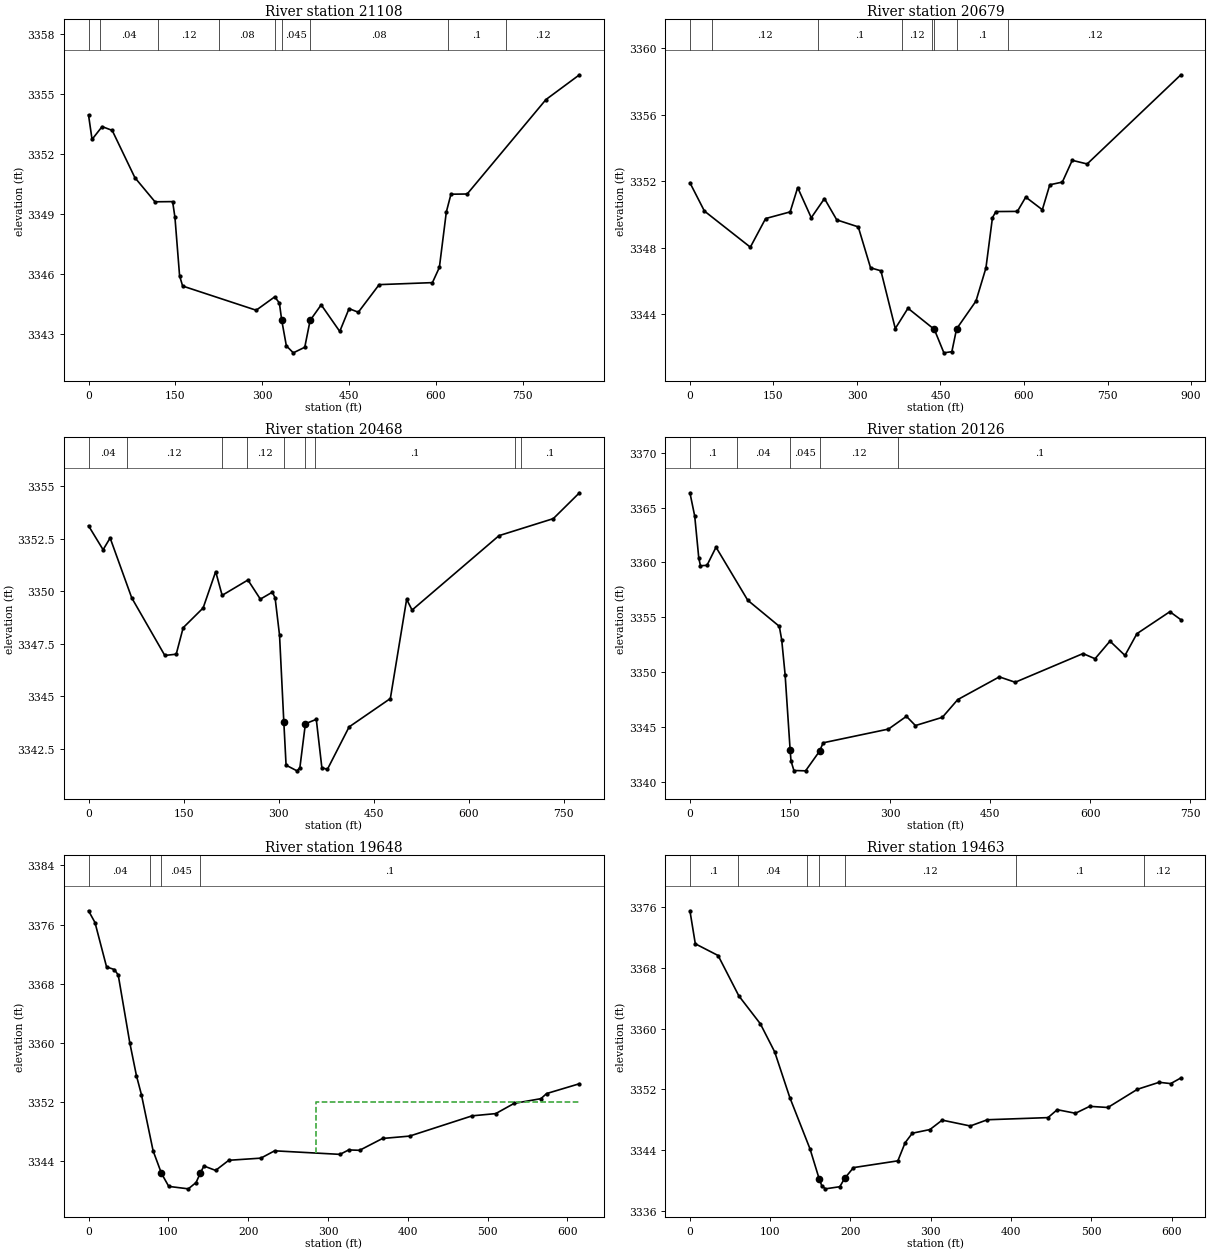
Type RM Length L Ch R = 1 ,21108   ,379.7,428.5,426.4
XS GIS Cut Line= 5
2173546.58071836 445217.868786822173680.31094461445274.884190809
2173847.41746561445285.3152235012173985.48544254 445294.79047682
2174382.09247432 445294.79047682
#Sta/Elev= 30
       0 3353.97    6.08 3352.75   23.47 3353.39   40.87  3353.2      80 3350.84
  114.79 3349.63  145.23 3349.64  149.25 3348.85  157.26 3345.93   162.5 3345.42
  289.52 3344.21  321.59 3344.88  329.61 3344.57 333.5853343.719  341.63 3342.43
  353.66 3342.08  373.42 3342.36  382.65  3343.7  401.78 3344.48  433.85 3343.15
  449.89 3344.29  465.89 3344.11  501.89 3345.49  593.89 3345.59  605.89 3346.35
  617.89 3349.12  625.89 3350.01  653.89 3350.02  789.89 3354.74  847.81 3355.98
#Mann= 9 ,-1,0
       0      .1       0      20     .04       0     120     .12       0
  225.38     .08       0  322.81      .1       0 333.585    .045       0
  382.65     .08       0   621.2      .1       0   721.2     .12       0
Bank Sta=333.585,382.65
XS Rating Curve= 0 ,0
Exp/Cntr(USF)=0,0
Exp/Cntr=0.3,0.1

Type RM Length L Ch R = 1 ,20679   ,194.9,211.5,221.4
XS GIS Cut Line= 4
2173525.25885277445381.4213643072173892.08651697445576.340861153
2173961.12050544445627.7779505982174131.67506518445967.533462461
#Sta/Elev= 30
       0  3351.9      26  3350.2   108.5 3348.03   135.9 3349.75     180 3350.15
   193.5 3351.61   217.9  3349.8   241.6 3350.95   263.7 3349.67   302.3 3349.25
   324.4 3346.79     343 3346.61   368.8 3343.14   391.6 3344.36   438.9 3343.09
   456.1 3341.68   470.4 3341.75   478.9 3343.12   513.7 3344.79   531.6 3346.78
   543.3  3349.8   549.5 3350.17   588.1 3350.18   603.1 3351.04   632.9 3350.28
   646.3 3351.78   668.8 3351.94   686.6 3353.25   713.4 3353.03   881.7 3358.39
#Mann= 8 ,-1,0
       0     .04       0      40     .12       0     230      .1       0
     380     .12       0   435.4      .1       0   438.9    .045       0
   478.9      .1       0  571.49     .12       0
Bank Sta=438.9,478.9
XS Rating Curve= 0 ,0
Exp/Cntr(USF)=0,0
Exp/Cntr=0.3,0.1

Type RM Length L Ch R = 1 ,20468   ,339.9,341.7,335.5
XS GIS Cut Line= 4
2173517.13720707445408.4935166472173707.99588106 445608.82744396
2173768.90822382 445752.309851362173892.08651697446071.761248968
#Sta/Elev= 30
       0 3353.11      23 3351.97    34.1 3352.53    68.2 3349.68   120.4 3346.94
   138.4    3347   149.4 3348.26   180.9  3349.2   200.7 3350.93   210.9  3349.8
   251.6 3350.53   271.2 3349.62   290.1 3349.95   294.5 3349.68   301.5  3347.9
  308.28 3343.76   311.8 3341.72     329 3341.45   333.6  3341.6   342.3 3343.69
   359.5  3343.9   368.3  3341.6     377 3341.52   411.3 3343.54   476.4 3344.89
   502.1 3349.61   510.7  3349.1   647.9 3352.64   733.6 3353.45   774.9 3354.68
#Mann= 9 ,-1,0
       0     .04       0      60     .12       0     210      .1       0
     250     .12       0  308.28    .045       0   342.3     .12       0
   356.7      .1       0  672.57     .12       0  682.57      .1       0
Bank Sta=308.28,342.3
XS Rating Curve= 0 ,0
Exp/Cntr(USF)=0,0
Exp/Cntr=0.3,0.1

Type RM Length L Ch R = 1 ,20126   ,497.1,478.7,462.6
XS GIS Cut Line= 4
2173315.44967214445527.6109869412173402.08055962445627.777950598
2173442.68878813445718.469660936 2173671.4484754446167.867389774
#Sta/Elev= 30
       0 3366.34     7.2 3364.21    13.3 3360.38    15.8  3359.7    25.6 3359.74
    39.1 3361.39    86.7 3356.56     134 3354.19   137.6 3352.96   142.7  3349.8
   150.2 3342.98   151.5 3341.95   155.9 3341.07   173.4 3341.04   194.5 3342.84
   199.7 3343.59   297.7 3344.84   324.6    3346   338.1 3345.16   378.5 3345.91
   401.5 3347.52   463.9 3349.59   487.7  3349.1   589.4 3351.71   607.4 3351.24
   629.8 3352.84   652.3 3351.54   670.2 3353.52   719.6 3355.52   736.1 3354.79
#Mann= 5 ,-1,0
       0      .1       0      70     .04       0   150.2    .045       0
   194.5     .12       0   311.8      .1       0
Bank Sta=150.2,194.5
XS Rating Curve= 0 ,0
Exp/Cntr(USF)=0,0
Exp/Cntr=0.3,0.1

Type RM Length L Ch R = 1 ,19648   ,188.6,184.7,180.4
XS GIS Cut Line= 4
 2173009.5343507445947.2293482062173056.91061729445979.715931013
2173211.22188563446088.0045403722173515.78359945446296.460113387
#Sta/Elev= 30
       0 3377.87     8.1 3376.28    22.6 3370.28    32.3 3369.93    37.2 3369.19
    51.7 3360.02      60 3355.59    66.3    3353    80.9 3345.42   91.393342.365
   100.5 3340.61     125 3340.28   134.7 3341.13  139.863342.363   144.5 3343.37
   159.2 3342.77   175.7 3344.14   215.9 3344.43   233.1 3345.42     315 3344.94
   325.9 3345.54   339.6 3345.49   368.3 3347.09   402.2 3347.41   480.6 3350.15
   510.1 3350.45   533.1 3351.83   566.7 3352.47   573.8 3353.16     615 3354.49
#Mann= 4 ,-1,0
       0     .04       0   77.44      .1       0   91.39    .045       0
  139.86      .1       0
#XS Ineff= 2 , 0
                          284.95         3352.01
Permanent Ineff=
       F       F
Bank Sta=91.39,139.86
XS Rating Curve= 0 ,0
Exp/Cntr(USF)=0,0
Exp/Cntr=0.3,0.1

Type RM Length L Ch R = 1 ,19463   ,431.7,443.6,439.8
XS GIS Cut Line= 3
 2172919.0885475446097.2365234542173004.54506988446160.020907247
2173452.75580974446393.718335809
#Sta/Elev= 30
       0 3375.48     6.7 3371.14    35.1  3369.6    60.9  3364.3    87.7 3360.63
   105.6 3356.93   124.4 3350.94   149.6 3344.18  160.88 3340.29   164.3 3339.33
   168.8 3338.94   186.7 3339.22   192.6  3340.3   203.7 3341.73     259 3342.62
     268 3344.99     277 3346.25   298.9 3346.73   314.2 3347.97   349.2  3347.2
   370.5 3348.02     446  3348.3   457.5 3349.34   480.2 3348.87   497.9 3349.78
   520.6 3349.63   557.3 3352.02   584.4 3352.94   598.8 3352.77   611.5 3353.51
#Mann= 7 ,-1,0
       0      .1       0      60     .04       0  146.04     .12       0
  160.88    .045       0   192.6     .12       0  406.04      .1       0
  566.04     .12       0
Bank Sta=160.88,192.6
XS Rating Curve= 0 ,0
Exp/Cntr(USF)=0,0
Exp/Cntr=0.3,0.1

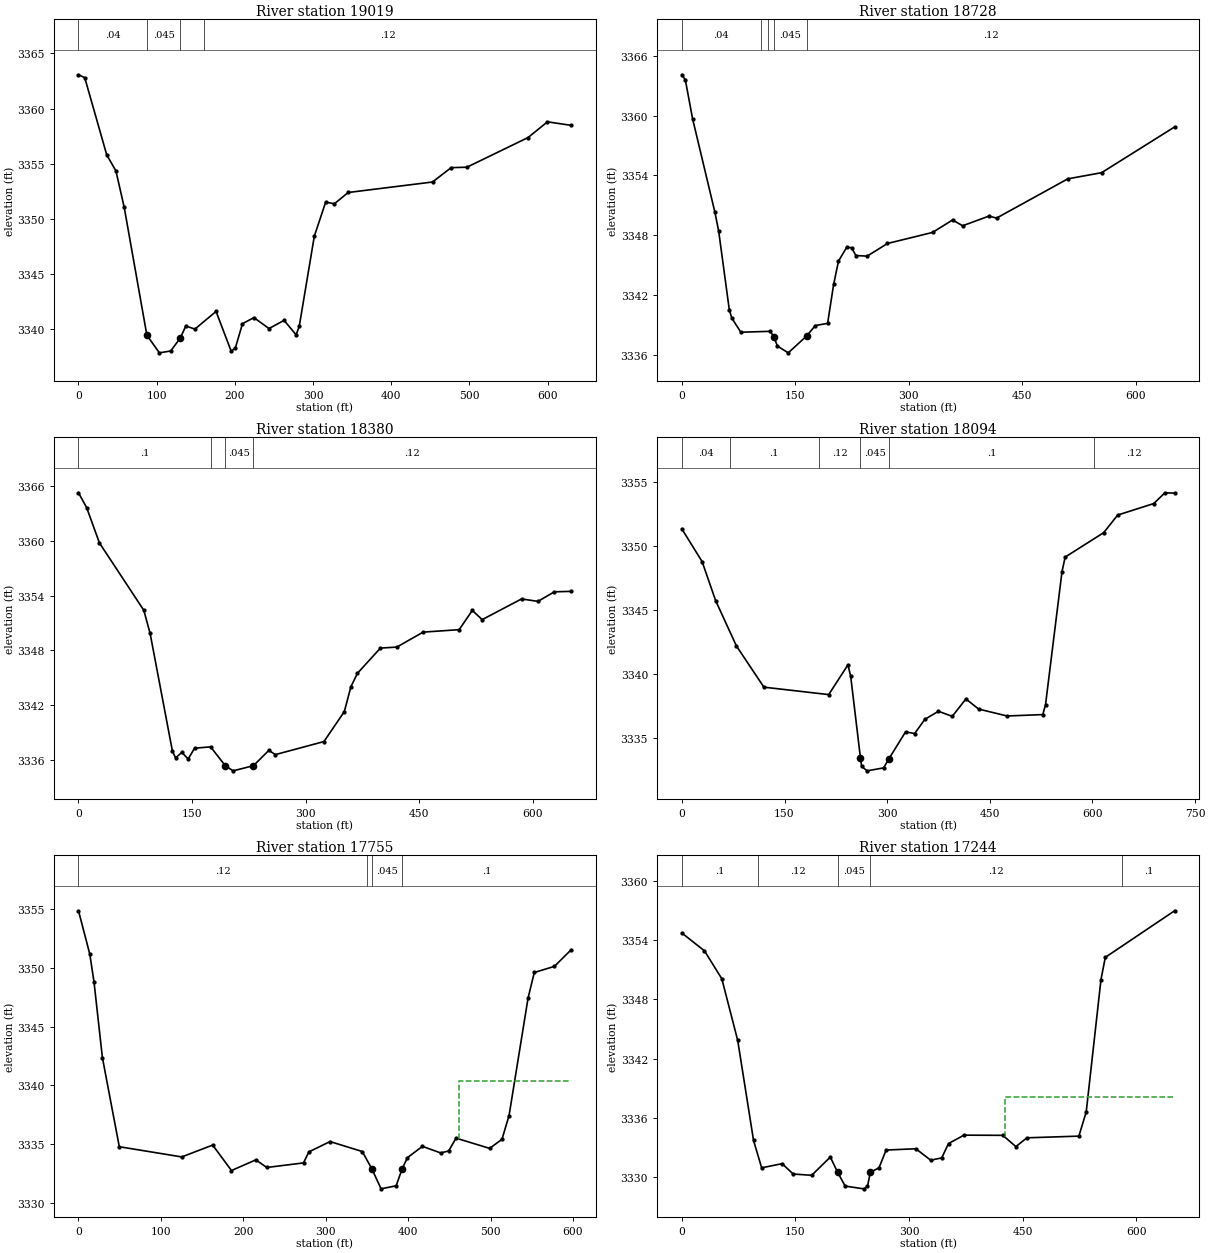
Type RM Length L Ch R = 1 ,19019   ,287,291.2,285.4
XS GIS Cut Line= 4
2172733.39839683446385.7982161082172792.95713198446423.699229383
2173016.30238878446575.3032824862173268.07340554446718.785689886
#Sta/Elev= 30
       0 3363.06       8  3362.8    36.1 3355.81    47.9 3354.35    58.5 3351.05
    87.5 3339.47   103.5 3337.88     118 3338.05   130.2 3339.22   137.3 3340.31
   148.9 3340.03     176 3341.63   195.3 3338.03   200.7 3338.33   209.8 3340.52
   224.4 3341.07   243.7 3340.08     263 3340.82   278.4 3339.51   282.4 3340.28
   301.7 3348.45   316.2 3351.53   327.4 3351.38     345  3352.4   452.9 3353.35
   476.7 3354.65   496.9 3354.69   575.2 3357.38   599.9  3358.8   630.3 3358.48
#Mann= 4 ,-1,0
       0     .04       0    87.5    .045       0   130.2     .04       0
   160.6     .12       0
Bank Sta=87.5,130.2
XS Rating Curve= 0 ,0
Exp/Cntr(USF)=0,0
Exp/Cntr=0.3,0.1

Type RM Length L Ch R = 1 ,18728   ,369.8,347.7,310.6
XS GIS Cut Line= 4
2172580.44073611 446609.143472912172657.59637028446663.287777589
2172769.94580249 446739.089804142173146.24872001446928.594870518
#Sta/Elev= 30
       0 3364.11     4.6  3363.6    14.2 3359.69    43.7  3350.3    48.7 3348.39
    62.7 3340.51    65.9  3339.7    77.9 3338.26   116.7 3338.35   121.5 3337.81
   126.3 3336.87   140.6 3336.19   164.9 3337.88   176.3 3338.93   192.6 3339.15
   200.6 3343.07     207  3345.4     218 3346.81   224.3 3346.74     230 3345.96
   244.9  3345.9   271.7 3347.17   331.3 3348.28   357.7 3349.53   371.1 3348.95
   405.8 3349.92   415.9 3349.72     510 3353.66   554.7 3354.28   651.1 3358.87
#Mann= 5 ,-1,0
       0     .04       0  104.26      .1       0  114.26     .12       0
   121.5    .045       0   164.9     .12       0
Bank Sta=121.5,164.9
XS Rating Curve= 0 ,0
Exp/Cntr(USF)=0,0
Exp/Cntr=0.3,0.1

Type RM Length L Ch R = 1 ,18380   ,273,286.5,295
XS GIS Cut Line= 4
2172409.83743451446965.753832588 2172576.4180953447017.714293215
 2172633.7715447446995.9954548892173016.75314451447155.850994628
#Sta/Elev= 30
       0 3365.27    10.8 3363.64    27.6 3359.78    86.3 3352.38    94.6 3349.85
     124 3336.97   128.2  3336.2   136.5  3336.8   144.9 3336.08   153.3 3337.26
   174.5 3337.41  193.74 3335.36   204.2 3334.78231.06123335.344   251.4 3337.02
   260.1 3336.56   324.2 3337.99   351.1 3341.27   359.8    3344   368.5 3345.48
   398.8 3348.24   420.5 3348.35   455.2 3349.99   502.8 3350.26   520.2 3352.37
   533.2 3351.36   585.2 3353.63   606.9 3353.36   628.5 3354.41   650.8 3354.46
#Mann= 4 ,-1,0
       0      .1       0   174.5     .12       0  193.74    .045       0
231.0612     .12       0
Bank Sta=193.74,231.0612
XS Rating Curve= 0 ,0
Exp/Cntr(USF)=0,0
Exp/Cntr=0.3,0.1

Type RM Length L Ch R = 1 ,18094   ,326.1,339.3,350.9
XS GIS Cut Line= 4
2172331.35695477447117.4827600882172490.06192491447258.747623621
2172828.39999313447283.1637728742172994.08100592447253.515591639
#Sta/Elev= 30
       0  3351.3    29.6 3348.75    49.3 3345.71    79.7 3342.17   119.9 3338.95
   214.6 3338.37   242.7 3340.69   246.7 3339.81  261.02 3333.41   262.7 3332.77
   270.7 3332.42   294.8 3332.65   302.8 3333.38   326.9 3335.46   340.2 3335.33
   355.1 3336.44     375 3337.07   395.1 3336.67   415.1 3338.03   433.7 3337.24
   475.3  3336.7   527.4 3336.81   531.4 3337.57   555.5 3347.96   560.1  3349.1
   616.5 3351.01   636.8 3352.38   689.6 3353.28   705.9 3354.12     720 3354.09
#Mann= 6 ,-1,0
       0     .04       0      70      .1       0     200     .12       0
  261.02    .045       0   302.8      .1       0  601.69     .12       0
Bank Sta=261.02,302.8
XS Rating Curve= 0 ,0
Exp/Cntr(USF)=0,0
Exp/Cntr=0.3,0.1

Type RM Length L Ch R = 1 ,17755   ,505.6,510.4,506.4
XS GIS Cut Line= 5
2172201.43060336 447367.16373842 2172459.9696582447572.912096202
2172543.89333046447618.9347551792172618.34174939447658.189376072
2172668.42523122447729.930579772
#Sta/Elev= 30
       0 3354.89    13.7  3351.2    18.8 3348.84      29 3342.38    49.5 3334.78
   125.3 3333.91   162.8 3334.92   185.6 3332.75   215.2 3333.66   228.4 3333.01
     273  3333.4   279.5 3334.34   305.2 3335.22   344.3 3334.37   355.9  3332.9
   367.1 3331.19   385.4 3331.45   392.6 3332.88   399.1 3333.85   417.3 3334.81
   439.5 3334.25   449.1 3334.42   458.1 3335.51   498.8 3334.64   513.8 3335.41
   522.4 3337.44   545.4 3347.43     553 3349.63   577.4 3350.15   597.8 3351.57
#Mann= 4 ,-1,0
       0     .12       0  350.42      .1       0   355.9    .045       0
   392.6      .1       0
#XS Ineff= 2 , 0
                          461.75         3340.41
Permanent Ineff=
       F       F
Bank Sta=355.9,392.6
XS Rating Curve= 0 ,0
Exp/Cntr(USF)=0,0
Exp/Cntr=0.3,0.1

Type RM Length L Ch R = 1 ,17244   ,299.9,308.1,314.8
XS GIS Cut Line= 4
2171907.69775047447614.8739323282172043.05851217447709.626465517
2172170.29762817447800.3181758552172439.66554395447989.823242232
#Sta/Elev= 30
       0 3354.73    29.9 3352.92    52.8 3350.09    73.8 3343.84    94.7 3333.71
   105.4 3330.94   132.4 3331.36   147.1 3330.31   171.5 3330.18   196.1 3332.03
   205.8 3330.48   215.7 3329.09   240.3 3328.81   245.2 3329.05   248.9 3330.48
   260.4 3330.94   269.8 3332.74   309.1 3332.87   328.7 3331.71   343.3 3331.95
   352.2  3333.4   372.7 3334.25   423.9 3334.23   441.2 3333.09   455.8 3333.98
   524.4 3334.15   534.1  3336.6   553.6 3350.01   559.3 3352.26   650.8 3356.98
#Mann= 5 ,-1,0
       0      .1       0     100     .12       0   205.8    .045       0
   248.9     .12       0  581.48      .1       0
#XS Ineff= 2 , 0
                          426.62          3338.1
Permanent Ineff=
       F       F
Bank Sta=205.8,248.9
XS Rating Curve= 0 ,0
Exp/Cntr(USF)=0,0
Exp/Cntr=0.3,0.1

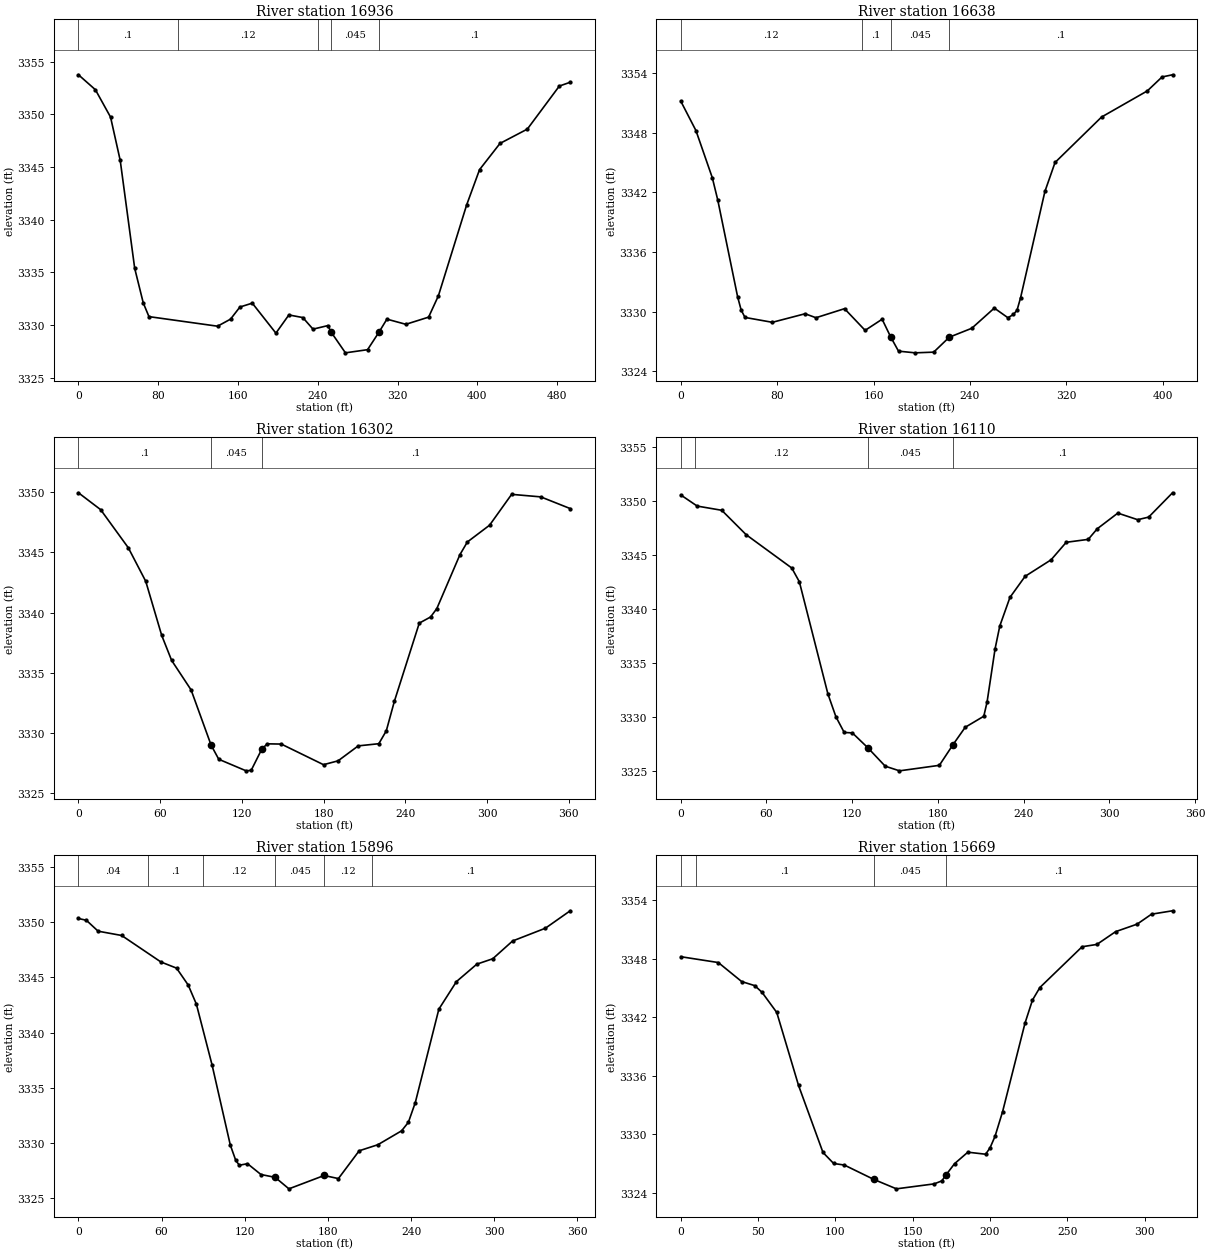
Type RM Length L Ch R = 1 ,16936   ,291.3,298,303.2
XS GIS Cut Line= 4
2171730.37515265447763.7707701962171879.27199052447954.629444191
2171937.47711805448020.9562174232172038.99768932448148.195333419
#Sta/Elev= 30
       0 3353.76      17 3352.34    32.2 3349.74    41.9 3345.62    56.4 3335.38
      65 3332.09    70.7 3330.79   139.5 3329.88   152.5 3330.55   161.9  3331.7
   174.3 3332.07     198 3329.22     211 3330.95     225  3330.7   235.2  3329.6
   250.2 3329.94     253 3329.37   267.7 3327.35   289.9 3327.65   301.2 3329.29
   309.3 3330.55   328.3 3330.06   351.1 3330.74   360.9 3332.76   389.3 3341.41
   402.2 3344.75   422.7 3347.24   450.1  3348.6   482.2 3352.69   493.1 3353.05
#Mann= 5 ,-1,0
       0      .1       0     100     .12       0     240      .1       0
     253    .045       0   301.2      .1       0
Bank Sta=253,301.2
XS Rating Curve= 0 ,0
Exp/Cntr(USF)=0,0
Exp/Cntr=0.3,0.1

Type RM Length L Ch R = 1 ,16638   ,337.6,336.4,335.9
XS GIS Cut Line= 4
 2171535.4556558447918.0820385322171613.96489759448065.625268783
 2171678.9380632448172.5602705252171737.14319073448272.727234182
#Sta/Elev= 30
       0 3351.16    12.6  3348.2    26.2 3343.45    30.7 3341.22    47.2 3331.48
    50.1 3330.16    53.3 3329.41      76 3328.92   103.2 3329.78   112.2 3329.38
   135.9 3330.29     153 3328.11   167.1 3329.23   174.2 3327.45   180.7 3326.02
   194.5 3325.85   209.9 3325.92   222.8 3327.42   241.5 3328.32   260.2 3330.35
   271.5 3329.38   276.1 3329.71   279.1 3330.15     282 3331.39   302.2 3342.08
   310.6 3344.99   349.2 3349.56   387.2 3352.19   399.4 3353.59   408.1 3353.81
#Mann= 4 ,-1,0
       0     .12       0     150      .1       0   174.2    .045       0
   222.8      .1       0
Bank Sta=174.2,222.8
XS Rating Curve= 0 ,0
Exp/Cntr(USF)=0,0
Exp/Cntr=0.3,0.1

Type RM Length L Ch R = 1 ,16302   ,194.9,191.7,191.4
XS GIS Cut Line= 4
2171251.19805624 448107.587104912171297.22071522 448179.32830861
2171374.37634938448287.6169179682171479.95774351448383.723058774
#Sta/Elev= 30
       0 3349.93    16.3 3348.53    36.6 3345.37    49.4 3342.59    61.1 3338.11
    68.4 3336.03    82.7 3333.58    97.3 3329.03    97.3 3329.02     103 3327.83
   123.1 3326.87   126.8 3326.91   134.6 3328.67   138.6 3329.11   148.9 3329.09
   179.9 3327.38   190.6  3327.7   205.4 3328.94   220.5 3329.12     226 3330.19
   231.9 3332.63   250.2 3339.12   258.5 3339.63   263.1 3340.33   280.1 3344.81
   285.5 3345.85   301.8 3347.24     318  3349.8   339.4 3349.59     361 3348.62
#Mann= 3 ,-1,0
       0      .1       0    97.3    .045       0   134.6      .1       0
Bank Sta=97.3,134.6
XS Rating Curve= 0 ,0
Exp/Cntr(USF)=0,0
Exp/Cntr=0.3,0.1

Type RM Length L Ch R = 1 ,16110   ,217.3,213.9,209.3
XS GIS Cut Line= 4
2171106.36204122448238.8870437572171165.92077637448318.749893159
2171251.19805624448406.7343882632171352.71862751448474.414769112
#Sta/Elev= 30
       0 3350.55    11.5 3349.52    28.7 3349.13    45.8 3346.87    77.7 3343.79
      83 3342.52     103 3332.14   108.6 3330.03   114.4 3328.58   120.1 3328.54
   130.9 3327.17   143.1 3325.46   153.1 3325.03     181 3325.54   190.6 3327.46
   199.1 3329.06   212.1 3330.08   214.4  3331.4     220 3336.32   223.3 3338.43
   230.4 3341.07     241 3343.02   259.2 3344.55   269.8 3346.17   285.2 3346.44
   291.5 3347.42   305.9 3348.87   319.8 3348.26   327.5  3348.5   344.2 3350.75
#Mann= 4 ,-1,0
       0      .1       0      10     .12       0   130.9    .045       0
   190.6      .1       0
Bank Sta=130.9,190.6
XS Rating Curve= 0 ,0
Exp/Cntr(USF)=0,0
Exp/Cntr=0.3,0.1

Type RM Length L Ch R = 1 ,15896   ,218.8,226.7,234
XS GIS Cut Line= 4
2170942.57551957448402.6735654122171004.84146995448470.353946261
2171126.66615547 448565.106479452171214.65065058448628.726037448
#Sta/Elev= 30
       0 3350.34     5.7 3350.18    14.2 3349.19    31.2  3348.8    59.5  3346.4
    70.8 3345.84    79.2 3344.31    85.1 3342.58    96.4 3337.08   109.6  3329.8
   113.5 3328.42   116.1 3327.97     122 3328.11   131.7 3327.13     142 3326.87
   151.9 3325.83   177.3 3327.04   187.6 3326.76   202.6 3329.28   216.1 3329.83
   233.2 3331.09   238.1 3331.86   243.1 3333.65   260.1 3342.12   272.8 3344.62
   287.5  3346.2     299 3346.69   313.3  3348.3     337 3349.46   354.9 3351.04
#Mann= 6 ,-1,0
       0     .04       0      50      .1       0      90     .12       0
     142    .045       0   177.3     .12       0  211.97      .1       0
Bank Sta=142,177.3
XS Rating Curve= 0 ,0
Exp/Cntr(USF)=0,0
Exp/Cntr=0.3,0.1

Type RM Length L Ch R = 1 ,15669   ,207.3,209,212.1
XS GIS Cut Line= 4
2170811.27558072448528.5590737912170858.65184731448604.361100342
2170931.74665863448707.2352792332170988.59817854448792.512559103
#Sta/Elev= 30
       0 3348.19    24.3 3347.59    39.4 3345.64    47.9 3345.22    52.6 3344.53
    62.1 3342.47    76.2 3334.98      92 3328.11    98.9 3326.98   105.8 3326.82
   124.7 3325.36   139.5 3324.38     164 3324.89   168.9  3325.2   171.4 3325.77
   177.1 3326.96   185.7 3328.14   197.2 3327.93   200.1  3328.6   203.3 3329.77
   208.2 3332.31   222.7 3341.39   227.5 3343.74   232.3 3345.03   259.6 3349.21
   269.2 3349.45   281.3 3350.76   295.2 3351.53   304.5 3352.55   318.1  3352.9
#Mann= 4 ,-1,0
       0     .04       0      10      .1       0   124.7    .045       0
   171.4      .1       0
Bank Sta=124.7,171.4
XS Rating Curve= 0 ,0
Exp/Cntr(USF)=0,0
Exp/Cntr=0.3,0.1

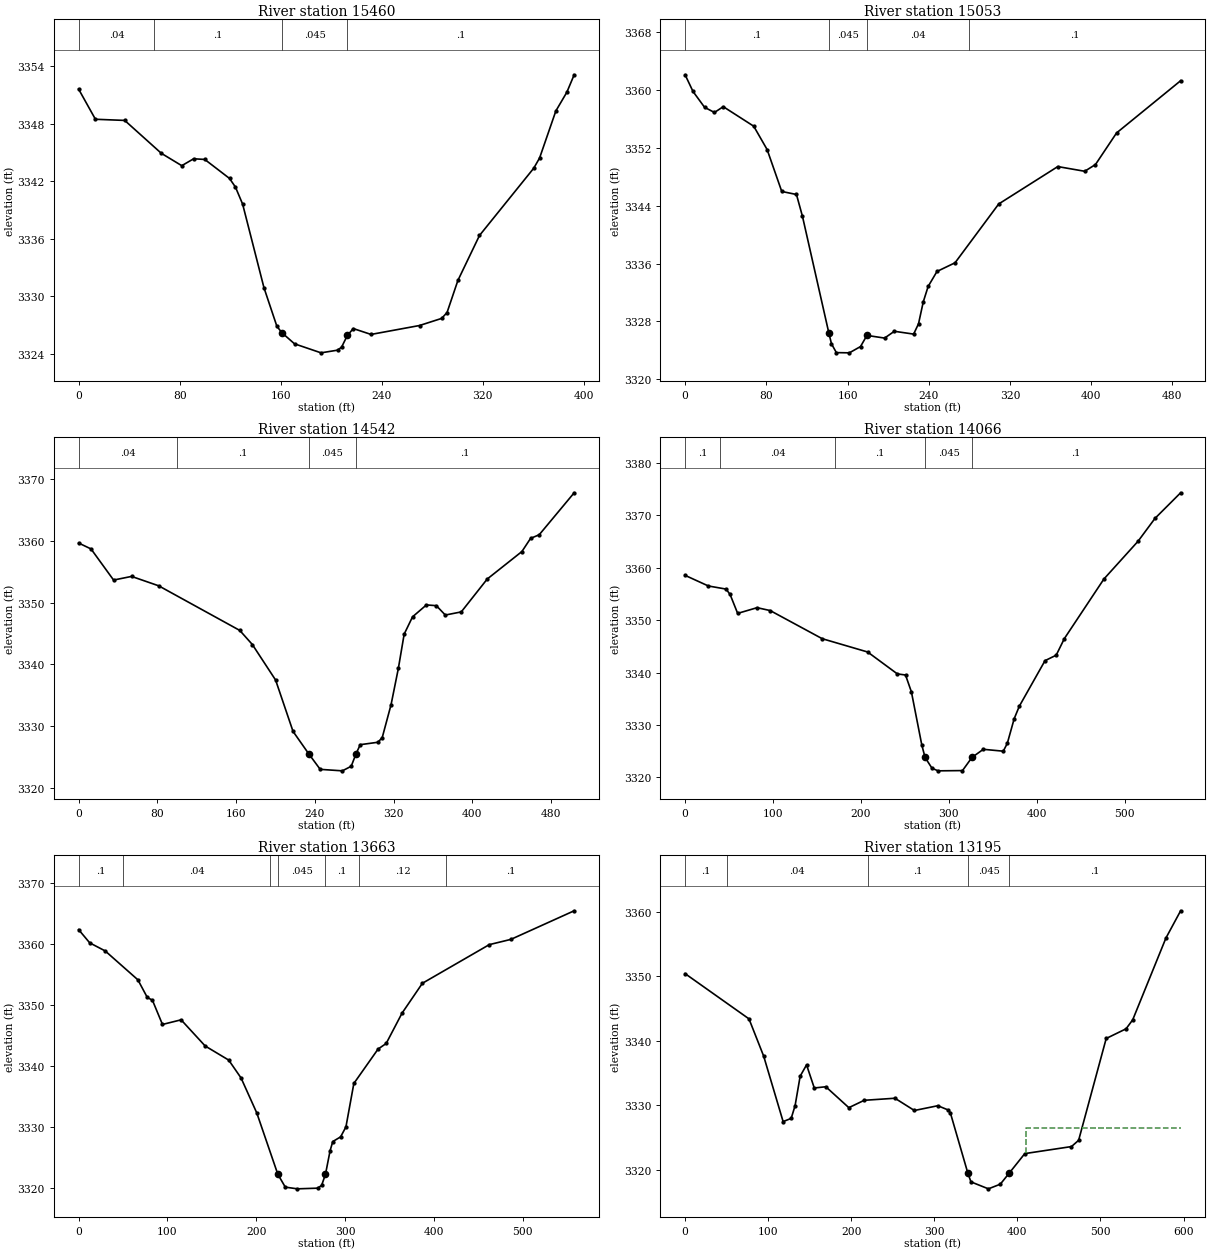
Type RM Length L Ch R = 1 ,15460   ,420,407.6,390.3
XS GIS Cut Line= 4
2170606.88083055448588.1178089382170678.62203425448701.820848765
2170757.13127604448833.1207876122170796.38589693448930.580536035
#Sta/Elev= 30
       0 3351.62    13.3 3348.48    36.5 3348.36    65.5 3344.93    81.7 3343.64
    91.1 3344.36    99.9 3344.29   119.5 3342.31   124.2 3341.41   129.9 3339.63
   146.8 3330.91     157  3326.9   160.9 3326.23     171 3325.06     192 3324.12
   205.1  3324.4   208.3 3324.72   212.9 3325.95   217.6 3326.65   231.6 3326.04
     270 3326.97   287.5 3327.71   291.8 3328.32   300.4 3331.67   317.5 3336.36
   360.5 3343.38   365.1 3344.44     378 3349.35   386.7  3351.3   392.5 3353.12
#Mann= 4 ,-1,0
       0     .04       0      60      .1       0   160.9    .045       0
   212.9      .1       0
Bank Sta=160.9,212.9
XS Rating Curve= 0 ,0
Exp/Cntr(USF)=0,0
Exp/Cntr=0.3,0.1

Type RM Length L Ch R = 1 ,15053   ,509.5,510.4,505.8
XS GIS Cut Line= 4
2170276.29989642 448928.770241872170353.16564932448981.178709753
2170510.39105296449082.5017476592170667.61645661449218.763764153
#Sta/Elev= 30
       0 3362.09     7.8 3359.78    19.2 3357.59    28.9 3356.88    37.6 3357.68
    67.6 3354.98    80.8 3351.75    95.2 3345.96   109.7 3345.54   115.6 3342.52
   141.5 3326.45   144.2 3324.89     149 3323.68   161.8 3323.65   172.8 3324.52
   179.1 3326.06   196.5 3325.69   206.1 3326.63   225.1 3326.24   229.9 3327.66
   234.6  3330.7   239.4 3332.83   248.1  3334.9   265.9  3336.1   308.9 3344.23
   367.1  3349.4   393.6 3348.75   404.2 3349.68     425 3354.05   488.1 3361.27
#Mann= 4 ,-1,0
       0      .1       0   141.5    .045       0   179.1     .04       0
  280.08      .1       0
Bank Sta=141.5,179.1
XS Rating Curve= 0 ,0
Exp/Cntr(USF)=0,0
Exp/Cntr=0.3,0.1

Type RM Length L Ch R = 1 ,14542   ,467.9,476.7,471.4
XS GIS Cut Line= 4
 2170049.1965356  449375.98916782170230.87922426449477.312205706
2170367.14124075449547.1901628832170496.41546153449606.586426483
#Sta/Elev= 30
       0 3359.66    12.6  3358.7    35.5 3353.66    53.8 3354.25    81.3 3352.73
   163.7  3345.5   176.5 3343.21   200.1 3337.46   217.8 3329.14  233.623325.539
   245.4 3322.99   267.9 3322.75   276.9 3323.49  281.873325.539   286.1 3326.99
     304 3327.38   308.4 3328.13   317.4 3333.48   324.8 3339.35   330.7  3344.9
   339.2  3347.7   353.3 3349.63   363.4 3349.51   372.5 3347.99   388.7  3348.5
   415.1 3353.83   450.3 3358.28   459.1 3360.41   467.9    3361   503.4  3367.8
#Mann= 4 ,-1,0
       0     .04       0     100      .1       0  233.62    .045       0
  281.87      .1       0
Bank Sta=233.62,281.87
XS Rating Curve= 0 ,0
Exp/Cntr(USF)=0,0
Exp/Cntr=0.3,0.1

Type RM Length L Ch R = 1 ,14066   ,381.1,402.8,421.3
XS GIS Cut Line= 4
2169787.15419619449718.3911579662169965.34298699 449854.65317446
 2170150.5195735449962.9640080842170262.32430499450018.866373825
#Sta/Elev= 30
       0 3358.57    26.5 3356.54    46.6 3355.95    51.2 3354.92    59.8 3351.31
    81.9  3352.4    96.8 3351.85     156 3346.48   207.7 3343.94   241.5 3339.76
   250.8 3339.55   257.5 3336.32   269.3  3326.2     273 3323.82   280.9 3321.76
   287.8 3321.26   315.6 3321.31   326.43323.822   339.3 3325.37     362 3325.01
   366.6 3326.51   374.4  3331.2   380.3 3333.61   409.5 3342.29   422.2 3343.33
   431.5  3346.5   476.5 3357.87   515.4 3365.09   534.6 3369.44   563.8 3374.33
#Mann= 5 ,-1,0
       0      .1       0      40     .04       0     170      .1       0
     273    .045       0   326.4      .1       0
Bank Sta=273,326.4
XS Rating Curve= 0 ,0
Exp/Cntr(USF)=0,0
Exp/Cntr=0.3,0.1

Type RM Length L Ch R = 1 ,13663   ,469.6,468,457.1
XS GIS Cut Line= 4
2169588.00201823449955.9762123662169699.80674972450078.262637425
 2169794.1419919450252.9575303672169884.98333623450424.158525449
#Sta/Elev= 30
       0 3362.32    12.5 3360.15    29.9 3358.83    66.7  3354.1    77.3 3351.21
    83.1 3350.75    94.4 3346.78   115.4 3347.54   142.5 3343.25     169 3340.94
   182.9 3338.01   200.6 3332.28  224.273322.238   232.7 3320.12   246.3 3319.84
     269 3319.95   273.6  3320.4  277.973322.236   283.2 3326.12   286.2 3327.59
     295 3328.36     301 3329.99   309.9 3337.11   337.2 3342.75   346.3 3343.66
   364.2 3348.64   387.1 3353.53   462.4 3359.86   486.7 3360.72     558 3365.41
#Mann= 7 ,-1,0
       0      .1       0      50     .04       0  215.69      .1       0
  224.27    .045       0  277.97      .1       0  315.69     .12       0
  414.23      .1       0
Bank Sta=224.27,277.97
XS Rating Curve= 0 ,0
Exp/Cntr(USF)=0,0
Exp/Cntr=0.3,0.1

Type RM Length L Ch R = 1 ,13195   ,206.7,227,250.1
XS GIS Cut Line= 4
2169301.39757687450218.6719106782169449.12656614450473.377064587
2169553.55567924450613.4648992362169629.96722542  450715.3469608
#Sta/Elev= 30
       0 3350.43    76.9 3343.42    94.6 3337.64     118  3327.5   127.7    3328
   132.4 3329.97   138.5 3334.54   146.2 3336.29   155.5 3332.71   169.4  3332.9
   197.1 3329.66   215.6  3330.8   252.6 3331.12     276 3329.22   304.2 3329.96
   316.5 3329.31   319.3 3328.86  340.32 3319.53   344.1 3318.16   365.1 3317.08
   379.4  3317.8  390.243319.527   408.9 3322.54   465.1 3323.63   473.7  3324.6
   506.9 3340.38   530.8 3341.88   538.8 3343.27   578.8 3355.95   596.5 3360.17
#Mann= 5 ,-1,0
       0      .1       0      50     .04       0     220      .1       0
  340.32    .045       0  390.24      .1       0
#XS Ineff= 2 , 0
                           409.9         3326.55
Permanent Ineff=
       F       F
Bank Sta=340.32,390.24
XS Rating Curve= 0 ,0
Exp/Cntr(USF)=0,0
Exp/Cntr=0.5,0.3