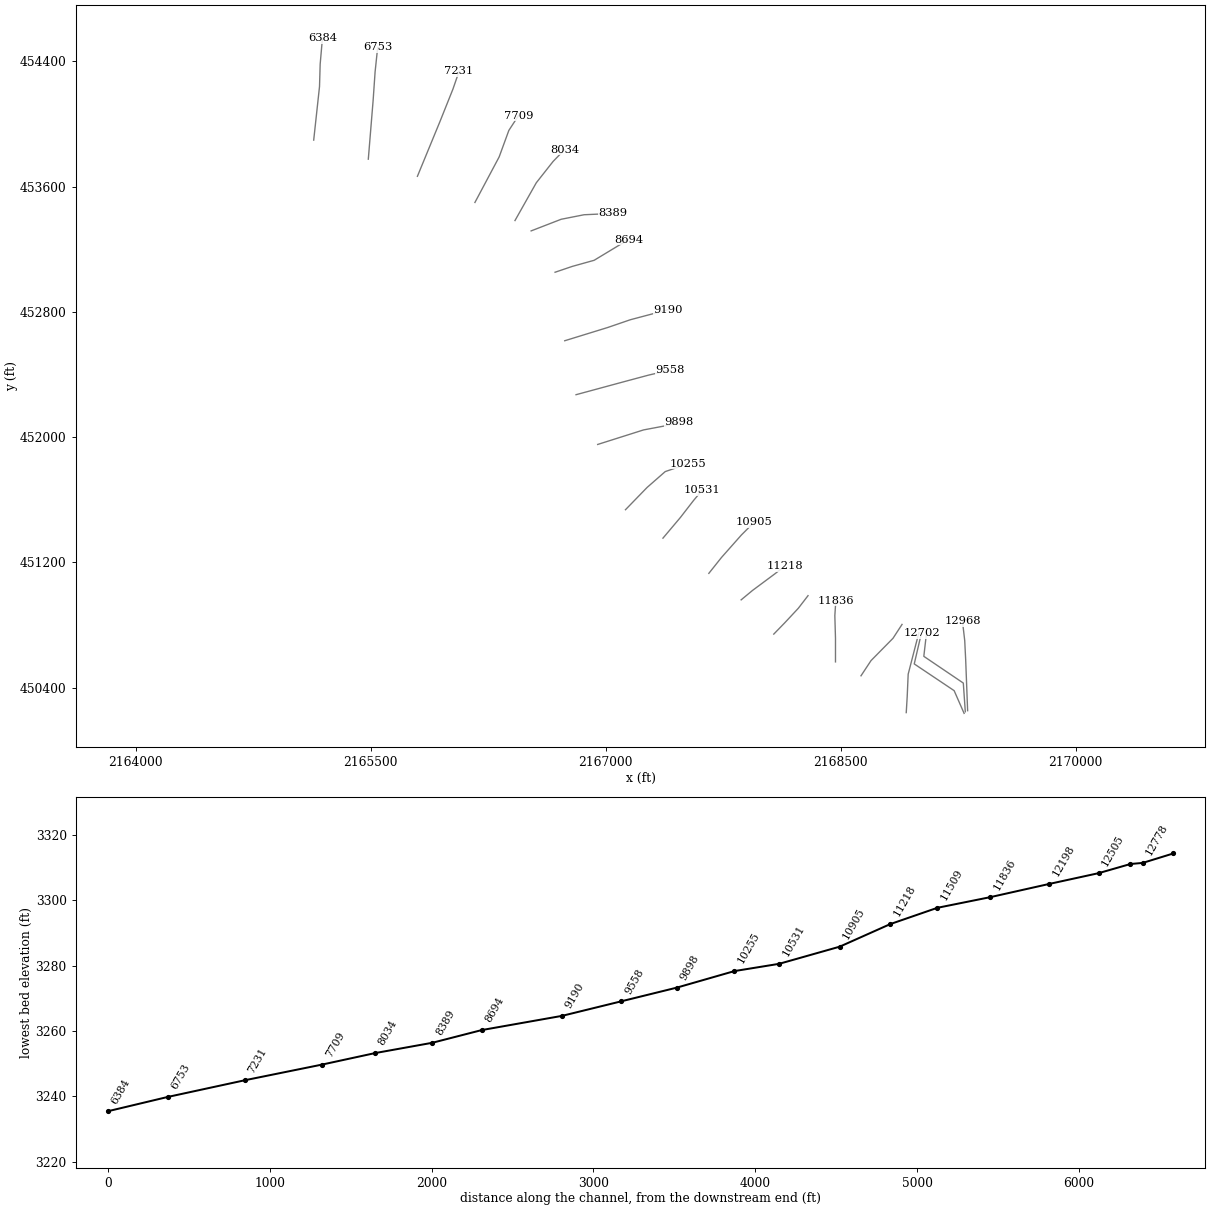
HEC-RAS study SFCRANBRYRV.prj: SFCRANBRYRV

--- SFCRANBRYRV.g01 (geometry) --- (continued)

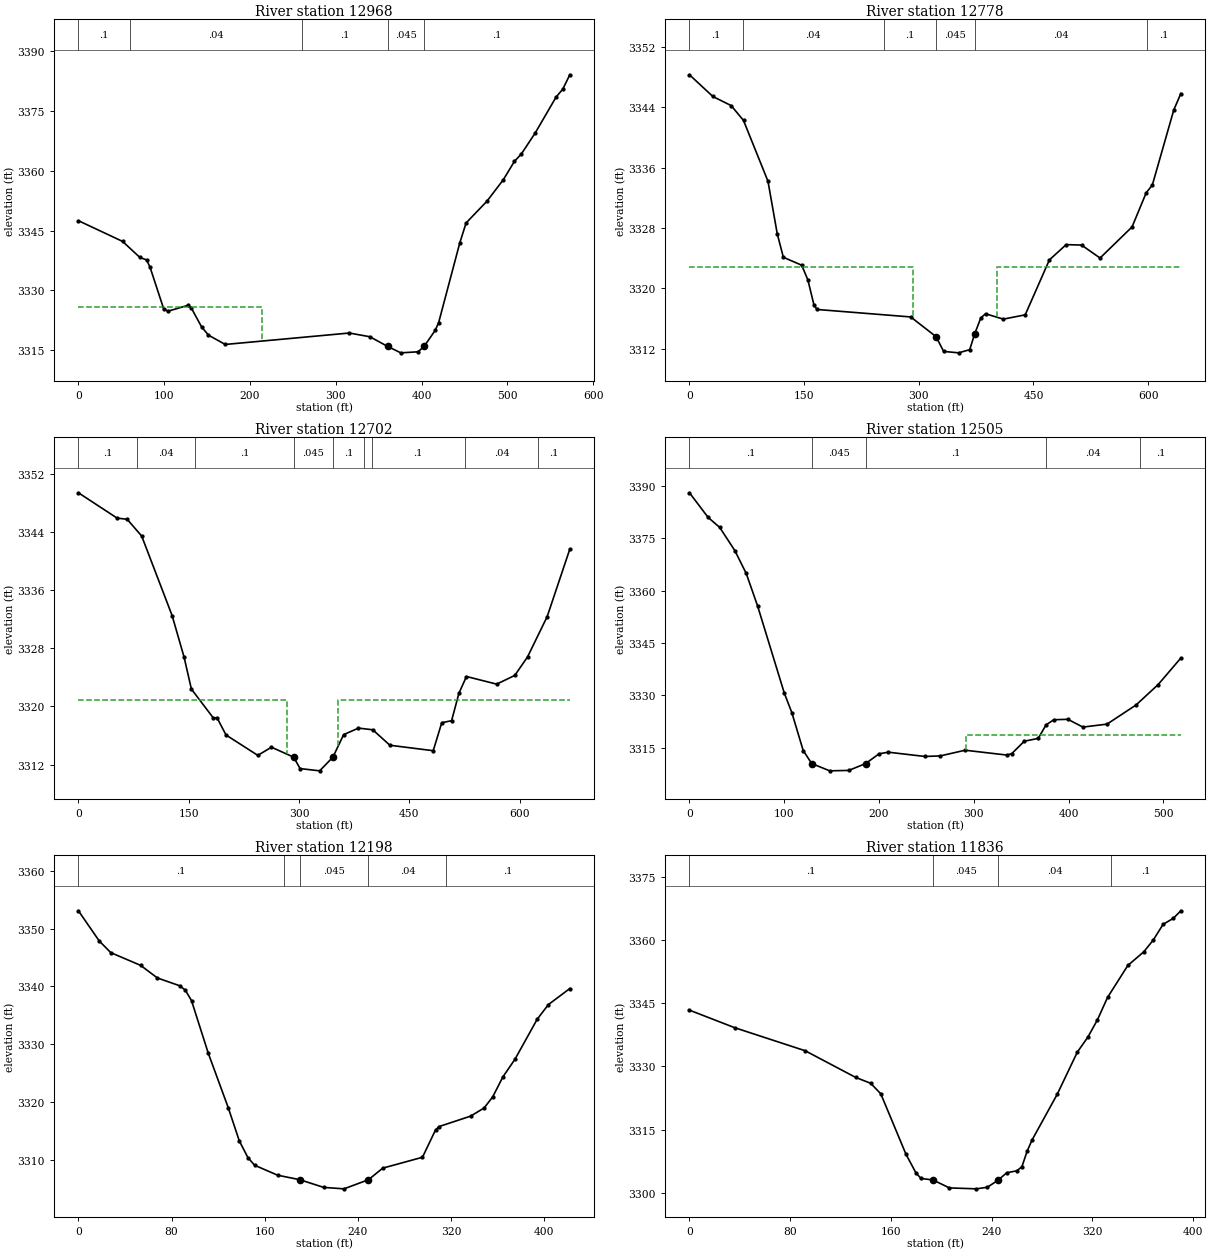
Type RM Length L Ch R = 1 ,12968   ,160.2,189.9,220.2
XS GIS Cut Line= 4
2169311.15278427450253.7448103712169298.77411379450577.653354597
2169292.58477855450701.4400593962169278.14299632450825.226764196
#Sta/Elev= 30
       0 3347.46    51.5 3342.27    71.5 3338.28    79.5 3337.63    83.5 3335.79
    99.5  3325.3   104.5  3324.8   127.5 3326.26   131.5 3325.63   143.5 3320.89
   151.5 3318.81   171.1 3316.47   315.7 3319.33   339.7  3318.4  360.413315.975
   375.7 3314.37   395.8 3314.63  402.893315.974   415.8    3320   419.8 3321.91
   444.4 3341.83   451.8 3346.89     476 3352.31   495.1 3357.68   508.2 3362.33
   516.3 3364.19   532.4 3369.43   556.7 3378.41   564.6 3380.43   572.7    3384
#Mann= 5 ,-1,0
       0      .1       0      60     .04       0     260      .1       0
  360.41    .045       0  402.89      .1       0
#XS Ineff= 2 , 0
          213.82 3325.91
Permanent Ineff=
       F       F
Bank Sta=360.41,402.89
XS Rating Curve= 0 ,0
Exp/Cntr(USF)=0,0
Exp/Cntr=0.5,0.3

Type RM Length L Ch R = 1 ,12778   ,75.4,75.5,76.4
XS GIS Cut Line= 4
2169296.30347379450246.689477608 2169283.5682161450430.077188422
2169031.41011373450600.7296415412169049.13759244450754.164026255
#Sta/Elev= 30
       0 3348.33    30.6 3345.45    54.6 3344.24    70.7 3342.27   102.7 3334.21
   114.8 3327.26   122.8 3324.13   146.8 3323.08   154.9 3321.13   162.9 3317.79
   166.9 3317.21   289.4 3316.22  322.563313.606   332.5 3311.65   352.1 3311.46
   366.6 3311.88   372.9 3313.92   381.1 3316.09   387.3 3316.64   410.6 3315.93
   439.2  3316.5   470.8 3323.78   492.8 3325.81   512.9 3325.75   537.1 3324.03
     579 3328.16   597.5 3332.69   605.5 3333.71   633.6 3343.68   642.8 3345.84
#Mann= 6 ,-1,0
       0      .1       0      70     .04       0  253.83      .1       0
  322.56    .045       0   372.9     .04       0  598.31      .1       0
#XS Ineff= 2 , 0
             292 3322.81     402         3322.81
Permanent Ineff=
       F       F
Bank Sta=322.56,372.9
XS Rating Curve= 0 ,0
Exp/Cntr(USF)=0,0
Exp/Cntr=0.5,0.3

Type RM Length L Ch R = 1 ,12702   ,232.9,197.2,156.3
XS GIS Cut Line= 4
2169288.66231918450236.501271451 2169224.9860307450381.683209179
2168970.28087679450552.3356622982169016.40798016450750.037802762
#Sta/Elev= 30
       0 3349.39    52.5 3345.91    66.3 3345.74      86 3343.44   127.4 3332.49
   143.6  3326.8   153.6 3322.38   183.6 3318.38   188.4 3318.44   200.7 3316.06
   243.9 3313.26   262.5 3314.38  292.673313.009   301.4 3311.44     328 3311.13
  345.963313.008   360.6 3316.11   380.8 3317.01   400.2 3316.78   423.5 3314.65
   482.4  3313.9     494 3317.75   507.4 3318.03   517.3 3321.79   527.6 3324.11
   568.7 3323.06   593.3 3324.26   610.6  3326.8   637.3 3332.34   668.1 3341.63
#Mann= 9 ,-1,0
       0      .1       0      80     .04       0  158.53      .1       0
  292.67    .045       0  345.96      .1       0  388.53     .04       0
  398.53      .1       0  525.12     .04       0  625.12      .1       0
#XS Ineff= 2 , 0
             284 3320.81     353         3320.81
Permanent Ineff=
       F       F
Bank Sta=292.67,345.96
XS Rating Curve= 0 ,0
Exp/Cntr(USF)=0,0
Exp/Cntr=0.5,0.3

Type RM Length L Ch R = 1 ,12505   ,332.1,307.1,277.5
XS GIS Cut Line= 4
 2168919.1615524450241.3661398912168925.35088764450344.521727224
2168931.54022288450486.8764377442168999.62291052450750.954741316
#Sta/Elev= 30
       0 3388.02    19.7 3380.95    31.9 3378.09    47.9 3371.44    59.9 3364.89
    71.9 3355.57     100 3330.66     108 3325.01     120 3314.14  129.013310.409
     148 3308.32   168.1 3308.44  185.923310.409   200.1 3313.21   209.9 3313.66
   248.4 3312.44   264.7  3312.6   290.9 3314.23     335 3312.84   340.2 3313.28
   353.3 3316.81     368 3317.62   376.3  3321.5   384.5 3322.97   399.3 3323.09
   415.1 3320.86   440.6 3321.71   471.3 3327.21   494.6 3333.06   518.5 3340.65
#Mann= 5 ,-1,0
       0      .1       0  129.01    .045       0  185.92      .1       0
  375.83     .04       0  475.83      .1       0
#XS Ineff= 2 , 0
                          291.75         3318.64
Permanent Ineff=
       F       F
Bank Sta=129.01,185.92
XS Rating Curve= 0 ,0
Exp/Cntr(USF)=0,0
Exp/Cntr=0.3,0.1

Type RM Length L Ch R = 1 ,12198   ,327.3,361.7,386.3
XS GIS Cut Line= 4
2168630.32590787 450476.560879012168694.28237202450573.527131103
2168834.57397079450715.881841623 2168892.3410997450804.595646729
#Sta/Elev= 30
       0 3353.09    17.9 3347.86    27.8 3345.85    53.4 3343.65    67.8 3341.47
      87 3340.12    91.8 3339.36    97.1 3337.55   111.5 3328.45   128.6 3319.06
   138.1 3313.31   145.5 3310.41   151.2 3309.09     171 3307.36  190.143306.577
   210.6 3305.25     228    3305  249.043306.577   261.3 3308.58   295.4 3310.46
   306.6 3315.18   309.6 3315.77   336.7 3317.57   348.3 3318.98   355.7  3320.9
   364.4 3324.34   374.9 3327.44   393.9 3334.33   403.5 3336.86   421.9 3339.64
#Mann= 5 ,-1,0
       0      .1       0  176.16     .04       0  190.14    .045       0
  249.04     .04       0  316.03      .1       0
Bank Sta=190.14,249.04
XS Rating Curve= 0 ,0
Exp/Cntr(USF)=0,0
Exp/Cntr=0.3,0.1

Type RM Length L Ch R = 1 ,11836   ,354,327.5,303.7
XS GIS Cut Line= 4
2168467.34007988450565.2746841172168467.34007988450715.881841623
2168463.21385639450860.2996638892168469.40319163450955.202804236
#Sta/Elev= 30
       0 3343.36    35.9  3339.2    91.9 3333.73   131.9 3327.42   143.9 3326.01
   151.9 3323.53   171.9  3309.2   179.9 3304.73   183.9 3303.44  193.373303.087
   206.4  3301.2   227.9 3300.98   236.6 3301.36   245.33303.088   251.9 3304.79
     260 3305.26     264 3306.23   268.1 3309.88     272 3312.54     292 3323.39
     308 3333.41   316.4 3336.98     324 3341.09     332 3346.38   348.1 3353.96
   360.8 3357.21   368.3 3359.99   376.1 3363.71   384.2 3365.14   390.2 3366.93
#Mann= 4 ,-1,0
       0      .1       0  193.37    .045       0   245.3     .04       0
  335.08      .1       0
Bank Sta=193.37,245.3
XS Rating Curve= 0 ,0
Exp/Cntr(USF)=0,0
Exp/Cntr=0.3,0.1

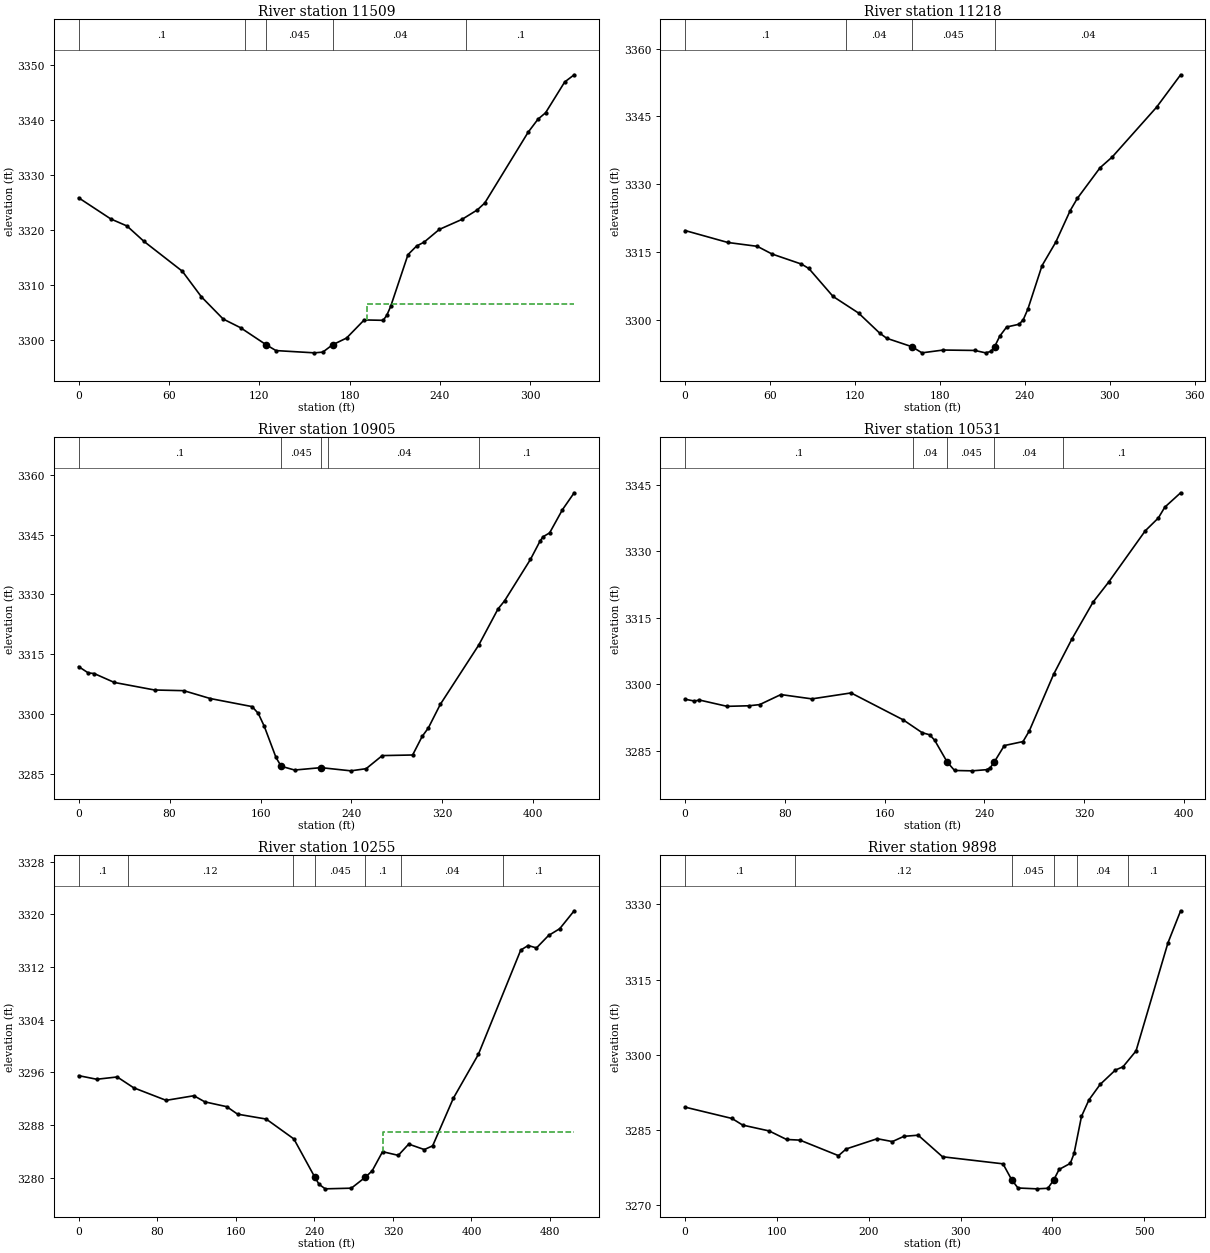
Type RM Length L Ch R = 1 ,11509   ,293.6,290.7,282.9
XS GIS Cut Line= 4
2168073.28573627 450742.702294332168143.43153566450814.911205463
2168230.08222902450907.7512340622168291.97558142450988.212592182
#Sta/Elev= 30
       0 3325.89    21.4 3322.04    32.1 3320.77    43.4 3317.97    68.9 3312.54
    81.5 3307.91      96 3303.86   107.6 3302.27  124.643299.168   131.1 3298.12
   156.6 3297.71   162.2 3297.84  168.663299.167     178  3300.4   189.7 3303.69
   202.3 3303.62   204.7 3304.52   207.3 3306.15   218.8 3315.56   224.5 3317.12
   229.5 3317.83   239.6 3320.14   254.7 3321.97   264.8 3323.68   269.8 3324.94
   298.6  3337.8   305.2 3340.19   310.2 3341.34   322.9 3346.94   329.2 3348.25
#Mann= 5 ,-1,0
       0      .1       0  110.67     .04       0  124.64    .045       0
  168.66     .04       0  257.67      .1       0
#XS Ineff= 2 , 0
                          191.36         3306.55
Permanent Ineff=
       F       F
Bank Sta=124.64,168.66
XS Rating Curve= 0 ,0
Exp/Cntr(USF)=0,0
Exp/Cntr=0.3,0.1

Type RM Length L Ch R = 1 ,11218   ,302.3,312.8,318.7
XS GIS Cut Line= 4
2167864.91144986450961.3921394762167937.12036099451021.222380129
2168081.53818326451128.5041909552168141.36842391451175.955761128
#Sta/Elev= 30
       0 3319.77    30.2 3317.13      51 3316.28    61.4 3314.58    82.2 3312.35
    87.4 3311.38   104.5  3305.2   122.5 3301.53   137.4  3297.1   142.4 3295.95
  160.183294.087   167.3 3292.73   182.3 3293.35   204.6 3293.26   212.2 3292.73
     216 3293.04  218.62 3294.09   222.2  3296.4   227.1 3298.44     236 3299.06
   238.9  3300.1   242.1  3302.4   252.1 3312.01   261.8  3317.2     272 3324.18
     277 3326.87   293.1 3333.66   301.7 3336.04     333 3347.04     350 3354.21
#Mann= 4 ,-1,0
       0      .1       0  113.78     .04       0  160.18    .045       0
  218.62     .04       0
Bank Sta=160.18,218.62
XS Rating Curve= 0 ,0
Exp/Cntr(USF)=0,0
Exp/Cntr=0.3,0.1

Type RM Length L Ch R = 1 ,10905   ,371.3,374.2,375.1
XS GIS Cut Line= 4
2167658.60027519451130.5673027022167739.06163331451231.659778288
 2167866.9745616451376.0776005542167947.43591972451456.538958674
#Sta/Elev= 30
       0 3311.92     8.5 3310.33    13.6 3310.19    31.4 3307.95    66.8 3306.06
    92.5 3305.89   115.8 3303.92   152.6  3301.9     158  3300.2   163.3 3296.97
   173.6 3289.16  178.143286.963     190 3286.01   213.2 3286.61   239.5 3285.81
   252.9 3286.35   267.1 3289.63   293.8 3289.78   302.2 3294.44   307.6 3296.54
   318.1 3302.44     352 3317.34   368.9 3326.36   374.7  3328.4   397.4 3338.75
   405.8 3343.31   408.5 3344.44   414.3 3345.41   425.6 3351.23   435.9 3355.46
#Mann= 5 ,-1,0
       0      .1       0  178.14    .045       0   213.2      .1       0
   219.2     .04       0  352.12      .1       0
Bank Sta=178.14,213.2
XS Rating Curve= 0 ,0
Exp/Cntr(USF)=0,0
Exp/Cntr=0.3,0.1

Type RM Length L Ch R = 1 ,10531   ,282.2,275.9,270.3
XS GIS Cut Line= 4
2167365.63840717451355.4464830882167477.04644149451487.485634874
 2167561.6340231451596.8305574472167617.33804026 451662.85013334
#Sta/Elev= 30
       0 3296.68     7.5 3296.27    11.5  3296.5    33.7 3295.08    51.3 3295.21
    59.8 3295.47    76.8 3297.73   101.7 3296.76   133.1  3298.1   174.9 3292.04
   190.1 3289.15   196.2 3288.67   200.2 3287.42  210.233282.522   216.1 3280.64
   230.2 3280.56   241.8 3280.82   244.6 3281.22  247.893282.525     256 3286.25
     271 3287.15     276 3289.53   295.5 3302.27   310.2 3310.24   327.2 3318.56
   339.8  3323.1     369 3334.59   379.5 3337.48   384.7 3339.92   397.4 3343.16
#Mann= 5 ,-1,0
       0      .1       0  182.76     .04       0  210.23    .045       0
  247.89     .04       0  302.76      .1       0
Bank Sta=210.23,247.89
XS Rating Curve= 0 ,0
Exp/Cntr(USF)=0,0
Exp/Cntr=0.3,0.1

Type RM Length L Ch R = 1 ,10255   ,375.7,357.1,336.4
XS GIS Cut Line= 4
2167126.31744455451537.0003167942167264.54593158451679.355027314
2167380.08018939  451780.44750292167524.49801166 451829.96218482
#Sta/Elev= 30
       0 3295.52    18.4 3294.97    39.3 3295.32      56 3293.68    89.1 3291.77
   117.4 3292.47   128.5 3291.54   150.8 3290.81   161.9 3289.67     191 3288.93
   219.2 3285.91  240.463280.119   244.8 3279.03   251.1 3278.34   277.7 3278.44
  292.08 3280.12   298.9 3281.07   309.5 3283.98   325.5 3283.42   336.1 3285.13
     352  3284.3   360.5 3284.87   381.6  3292.1     407 3298.73   450.2 3314.58
   457.8 3315.27   466.2  3314.9   478.5 3316.79   489.9 3317.82   504.6 3320.54
#Mann= 7 ,-1,0
       0      .1       0      50     .12       0  218.42      .1       0
  240.46    .045       0  292.08      .1       0  328.42     .04       0
  431.94      .1       0
#XS Ineff= 2 , 0
                          310.23         3286.91
Permanent Ineff=
       F       F
Bank Sta=240.46,292.08
XS Rating Curve= 0 ,0
Exp/Cntr(USF)=0,0
Exp/Cntr=0.3,0.1

Type RM Length L Ch R = 1 ,9898    ,337.1,340.7,342.7
XS GIS Cut Line= 4
2166948.88983434451953.7488896192167241.85170237452046.588918219
2167384.20641289452073.409370926 2167468.7939945452096.103600139
#Sta/Elev= 30
       0 3289.56    51.1  3287.3    62.7 3285.98    91.6 3284.81   110.5 3283.11
   125.1 3282.98   167.1 3279.88   175.5 3281.22   209.3 3283.26   225.8 3282.69
   238.4 3283.74   253.9 3283.96   280.4 3279.66   346.3 3278.25  355.753275.071
   362.6 3273.43     383 3273.26   395.2 3273.37  401.693275.073   407.4 3277.13
   419.6 3278.34   423.7 3280.32   431.8 3287.72   439.9    3291   452.1 3294.09
   468.7 3296.96     477 3297.61   491.2 3300.77     526 3322.35   539.8 3328.74
#Mann= 6 ,-1,0
       0      .1       0     120     .12       0  355.75    .045       0
  401.69     .12       0  427.32     .04       0  482.18      .1       0
Bank Sta=355.75,401.69
XS Rating Curve= 0 ,0
Exp/Cntr(USF)=0,0
Exp/Cntr=0.3,0.1

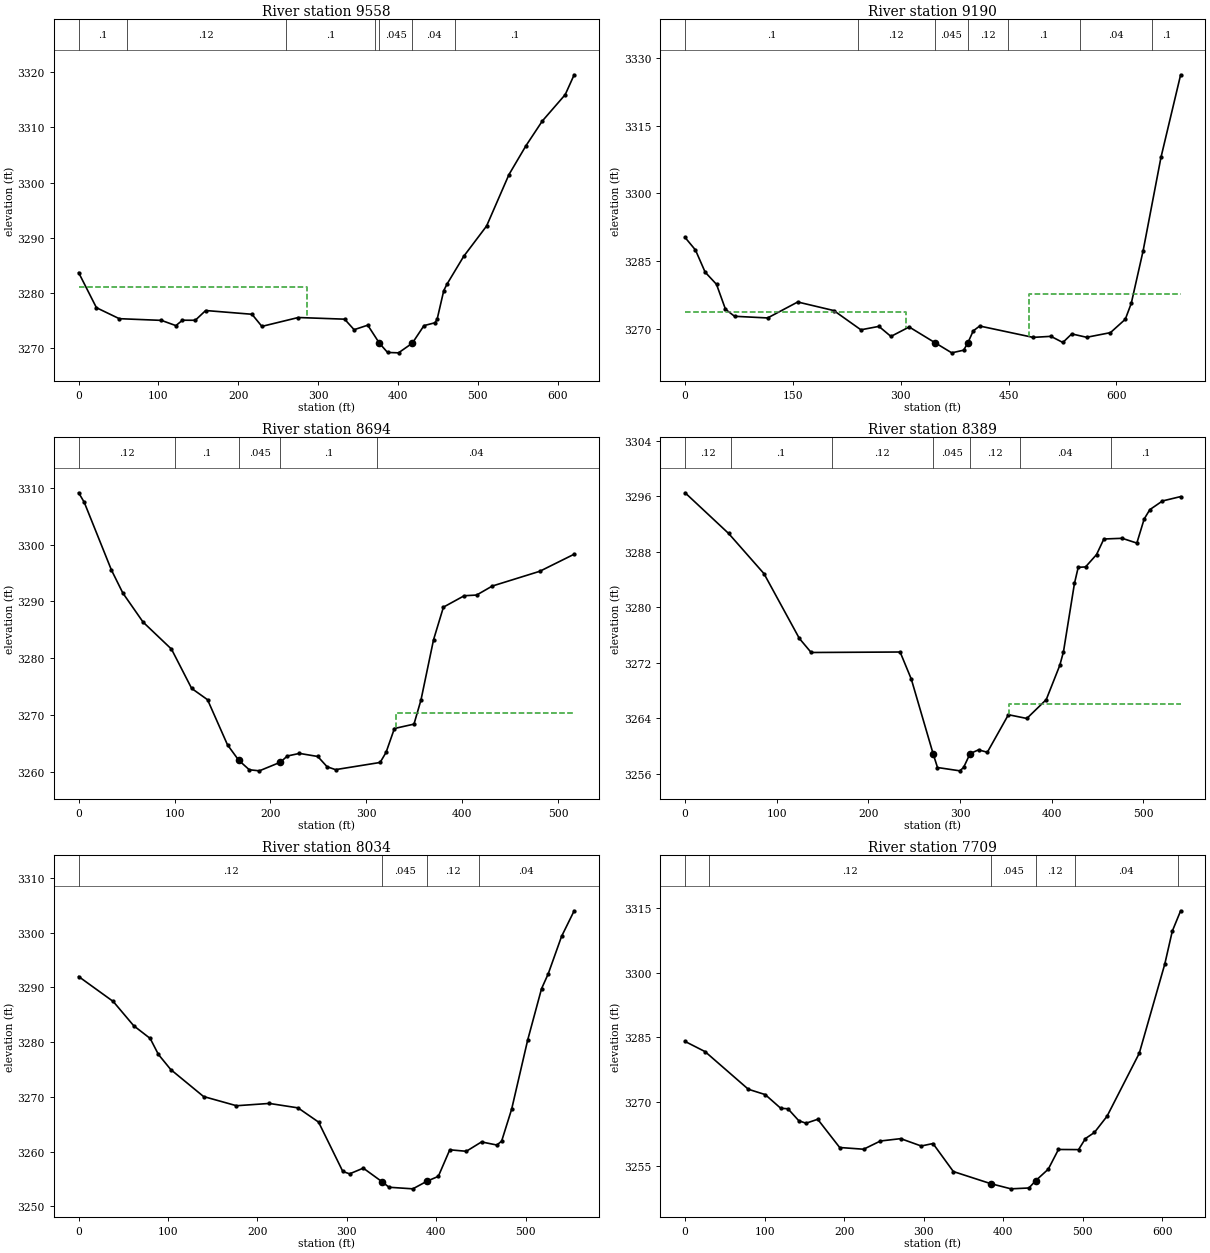
Type RM Length L Ch R = 1 ,9558    ,365,367.3,369.5
XS GIS Cut Line= 4
2166810.66134731452271.4680986052167130.44366805452358.118791965
2167276.92460206452397.3179151512167411.02686559452428.264591351
#Sta/Elev= 30
       0 3283.66    22.3 3277.29    50.9  3275.3   103.7 3274.99   121.8 3274.04
     130 3275.02   146.1 3275.01   159.1 3276.78   217.1  3276.1   229.5  3273.9
   275.1 3275.51   333.1 3275.21     345  3273.3   362.1 3274.12  376.673270.847
   386.9 3269.17   400.6  3269.1  417.843270.846   432.5 3274.04   446.3 3274.56
     449 3275.21   457.3 3280.41   461.5 3281.61   482.2  3286.6   510.9 3292.11
   538.9 3301.44   560.2 3306.68   580.7 3311.17   609.4 3315.96   620.6 3319.56
#Mann= 7 ,-1,0
       0      .1       0      60     .12       0     260      .1       0
  371.31     .04       0  376.67    .045       0  417.84     .04       0
  471.31      .1       0
#XS Ineff= 2 , 0
          286.02 3280.96
Permanent Ineff=
       F       F
Bank Sta=376.67,417.84
XS Rating Curve= 0 ,0
Exp/Cntr(USF)=0,0
Exp/Cntr=0.3,0.1

Type RM Length L Ch R = 1 ,9190    ,491.8,495.9,486.2
XS GIS Cut Line= 4
2166738.45243618452616.0077602972167012.84629849 452700.59534191
2167157.26412075 452750.110023832167398.64819511452814.066487977
#Sta/Elev= 30
       0 3290.22    14.4 3287.45    27.9 3282.53    43.7 3279.83    56.2 3274.29
    68.8 3272.74   114.8 3272.37   156.7 3275.91   206.9 3274.01   244.6 3269.74
   269.7  3270.5   286.4 3268.27   311.8 3270.37  347.633266.887     371 3264.63
   387.6 3265.22  393.553266.885   400.9  3269.5   409.9 3270.58   484.2 3268.06
     509 3268.29   525.6 3266.93     538 3268.83   558.7 3268.08   591.8 3269.11
   612.5 3272.08   620.8 3275.61   637.3 3287.27   662.1 3307.97   689.5 3326.32
#Mann= 7 ,-1,0
       0      .1       0     240     .12       0  347.63    .045       0
  393.55     .12       0  449.81      .1       0  549.81     .04       0
  649.81      .1       0
#XS Ineff= 2 , 0
          308.03 3273.68  478.49         3277.66
Permanent Ineff=
       F       F
Bank Sta=347.63,393.55
XS Rating Curve= 0 ,0
Exp/Cntr(USF)=0,0
Exp/Cntr=0.3,0.1

Type RM Length L Ch R = 1 ,8694    ,307.3,305.6,302.3
XS GIS Cut Line= 4
2166676.55908378453053.3874505892166785.90400635453090.523462029
2166926.19560513453129.7225852162167144.88545027453261.761737002
#Sta/Elev= 30
       0 3309.08     5.8 3307.43    34.2 3295.52    46.1 3291.48    67.2 3286.38
    96.8 3281.64   117.8 3274.75   134.4 3272.76   155.2 3264.84  166.943262.127
   177.9 3260.47   188.4 3260.28   210.4  3261.8   217.5 3262.88   230.2 3263.34
   249.3  3262.8     259    3261   267.8 3260.49   314.3 3261.75   320.5 3263.52
   329.2 3267.71   349.6 3268.48   356.9 3272.72     370 3283.29   380.3 3289.01
     402 3291.01   414.9 3291.13   431.2 3292.71   480.7  3295.3   516.6  3298.3
#Mann= 5 ,-1,0
       0     .12       0     100      .1       0  166.94    .045       0
   210.4      .1       0  311.14     .04       0
#XS Ineff= 2 , 0
                          331.35         3270.45
Permanent Ineff=
       F       F
Bank Sta=166.94,210.4
XS Rating Curve= 0 ,0
Exp/Cntr(USF)=0,0
Exp/Cntr=0.3,0.1

Type RM Length L Ch R = 1 ,8389    ,330.4,354.9,375.4
XS GIS Cut Line= 4
2166523.88881453453317.4657541622166715.75820697453391.737777042
2166862.23914098453420.6213414952167047.91919818453428.873788482
#Sta/Elev= 30
       0 3296.52    47.5 3290.65    86.1 3284.85   124.7  3275.5   137.6 3273.47
   234.7 3273.54   246.9 3269.63  270.673258.881   275.5 3256.87   299.9 3256.39
     304 3256.88   311.1 3258.88   320.3 3259.42   329.9 3259.07   352.9 3264.49
     373 3263.95   394.2 3266.67     409 3271.62     413 3273.57     425 3283.44
   429.1 3285.76   437.1 3285.82   449.1  3287.6   457.1 3289.85   477.1 3289.95
   493.1 3289.26   501.1 3292.74   507.3 3294.09   521.1 3295.34   540.9 3295.97
#Mann= 7 ,-1,0
       0     .12       0      50      .1       0     160     .12       0
  270.67    .045       0   311.1     .12       0  365.04     .04       0
  465.04      .1       0
#XS Ineff= 2 , 0
                          353.14         3265.98
Permanent Ineff=
       F       F
Bank Sta=270.67,311.1
XS Rating Curve= 0 ,0
Exp/Cntr(USF)=0,0
Exp/Cntr=0.3,0.1

Type RM Length L Ch R = 1 ,8034    ,312.7,324.6,336
XS GIS Cut Line= 4
 2166420.7332272453383.4853300552166556.89860247453624.869404414
 2166664.1804133453761.0347796942166736.38932443453835.306802574
#Sta/Elev= 30
       0    3292    38.7 3287.44    61.6 3283.01      80 3280.69    89.2 3277.77
     103 3275.01   139.7 3270.08   176.5  3268.4   213.2 3268.82   245.3 3268.01
   268.3 3265.41   295.4 3256.39     303 3255.96   318.3    3257   339.5 3254.49
   347.1 3253.51   373.7 3253.22   389.6 3254.62   402.2  3255.5     415 3260.35
   433.5 3260.08   450.5 3261.79   467.7 3261.22     473 3261.94   484.2 3267.78
   502.1 3280.39   517.6 3289.77   525.1  3292.5     540 3299.33   554.1 3304.01
#Mann= 4 ,-1,0
       0     .12       0   339.5    .045       0   389.6     .12       0
  447.14     .04       0
Bank Sta=339.5,389.6
XS Rating Curve= 0 ,0
Exp/Cntr(USF)=0,0
Exp/Cntr=0.3,0.1

Type RM Length L Ch R = 1 ,7709    ,472.2,478.6,468.3
XS GIS Cut Line= 4
2166164.90737061453499.0195878682166319.64075161453789.918344147
2166381.53410401453959.0935073732166443.42745641 454053.99664772
#Sta/Elev= 30
       0 3283.99    25.1 3281.63    79.5 3272.88   100.7 3271.64   120.2 3268.46
   129.3 3268.34   142.9 3265.57     152 3264.98   166.7  3265.9   194.3 3259.34
   224.4 3258.94   245.5 3260.85     271  3261.4   296.8 3259.69   311.6 3260.26
   337.2 3253.75   384.1 3250.94   409.6 3249.73   432.2 3249.93  440.913251.667
   456.5  3254.3   469.3 3258.88   494.6 3258.85   503.3 3261.43   514.5 3262.83
   530.4 3266.61   570.9 3281.25   602.9 3301.93   612.4 3309.63   622.9 3314.37
#Mann= 6 ,-1,0
       0      .1       0      30     .12       0   384.1    .045       0
  440.91     .12       0  489.49     .04       0  619.63      .1       0
Bank Sta=384.1,440.91
XS Rating Curve= 0 ,0
Exp/Cntr(USF)=0,0
Exp/Cntr=0.3,0.1

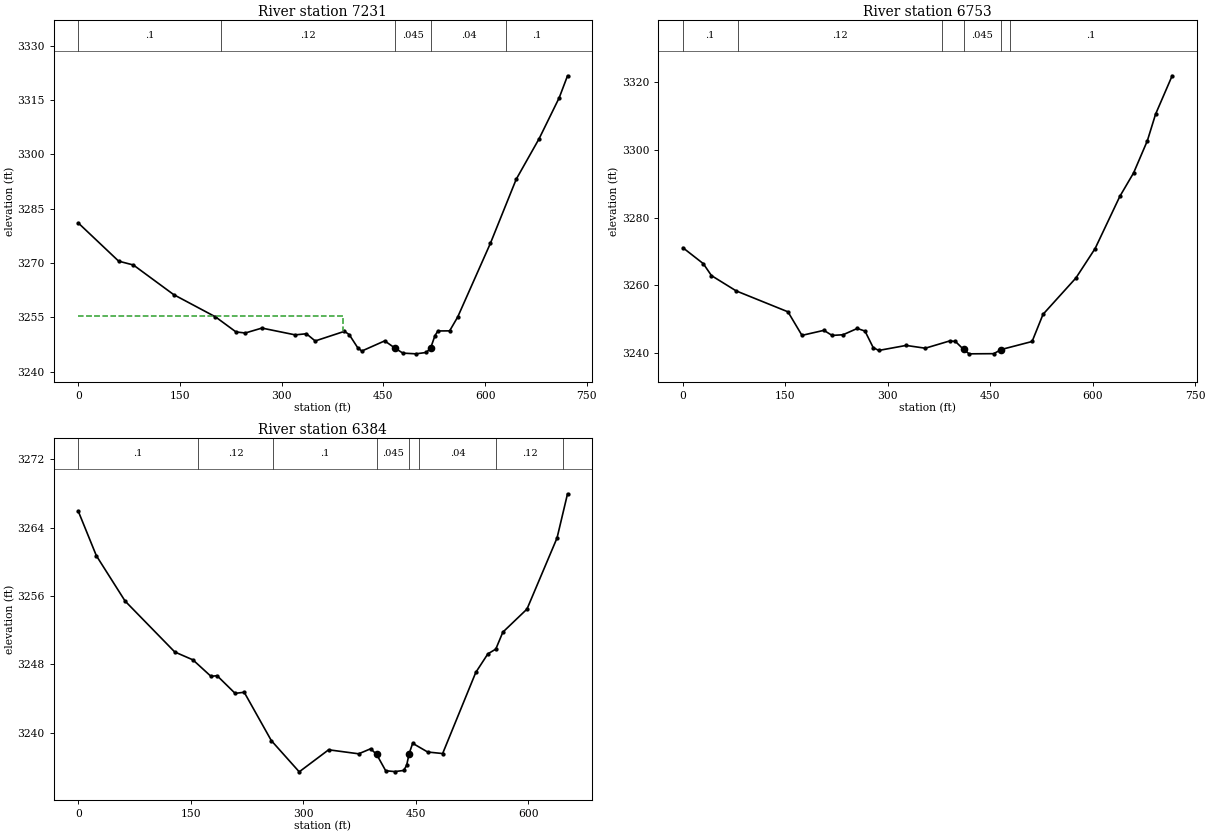
Type RM Length L Ch R = 1 ,7231    ,466.8,477.8,489.5
XS GIS Cut Line= 4
 2165797.6734797453666.1316393482165942.09130197 454016.86063628
2166024.61577184454223.1718109462166063.81489502454336.642957012
#Sta/Elev= 30
       0 3281.07    59.5 3270.53    81.2 3269.47   140.7 3261.28   202.3 3255.14
   232.6 3250.97   246.3 3250.68   270.8 3252.04   319.9 3250.16   336.4 3250.47
   349.4 3248.48   392.6 3251.14   399.6 3250.23   411.9 3246.67   418.1 3245.69
   451.9  3248.5   467.3 3246.48   478.7 3245.12   498.1 3244.92   513.5 3245.31
  519.813246.601   526.1 3249.97   530.4 3251.24   547.7 3251.27   559.6  3255.1
   607.9 3275.49   645.9 3293.16   679.8 3304.41   709.4 3315.72   721.6 3321.75
#Mann= 5 ,-1,0
       0      .1       0     210     .12       0   467.3    .045       0
  519.81     .04       0   631.5      .1       0
#XS Ineff= 2 , 0
          390.76  3255.3
Permanent Ineff=
       F       F
Bank Sta=467.3,519.81
XS Rating Curve= 0 ,0
Exp/Cntr(USF)=0,0
Exp/Cntr=0.3,0.1

Type RM Length L Ch R = 1 ,6753    ,363.3,368.5,362
XS GIS Cut Line= 4
2165484.08049421453775.4765619212165515.02717041454153.026011559
2165527.40584089454332.5167335192165543.91073486454489.313226265
#Sta/Elev= 30
       0 3271.08    29.8 3266.39    41.8 3262.86      78 3258.35   153.8 3252.18
   174.3 3245.24   206.4 3246.72   218.4 3245.22   234.5 3245.42   255.3 3247.28
   266.6  3246.5   278.6 3241.64   286.7 3240.79   326.8 3242.27   354.9 3241.45
   390.7  3243.6     399 3243.45     411 3241.08   419.1 3239.79   455.1 3239.84
  466.213241.068   511.3 3243.43   527.3 3251.44   575.5 3262.17   603.6 3270.85
   639.8 3286.24     660 3293.18   680.1 3302.65   692.1 3310.47   716.4  3321.8
#Mann= 6 ,-1,0
       0      .1       0      80     .12       0  378.82     .04       0
     411    .045       0  466.21     .04       0  478.82      .1       0
Bank Sta=411,466.21
XS Rating Curve= 0 ,0
Exp/Cntr(USF)=0,0
Exp/Cntr=0.3,0.1

Type RM Length L Ch R = 1 ,6384    ,247.3,248.6,242.1
XS GIS Cut Line= 4
2165135.41460903453897.2001549742165172.55062047454239.676704919
2165176.67684396454382.0314154392165191.11862619454547.080355172
#Sta/Elev= 30
       0 3265.91    24.1 3260.71    62.4 3255.41   128.7 3249.45   152.9 3248.53
     177  3246.6   185.1 3246.68   209.2 3244.61   221.3 3244.74   257.5 3239.08
   294.7 3235.43   333.9 3238.01     374 3237.54     390 3238.13     398 3237.46
     410 3235.56     422 3235.46     434 3235.59     438 3236.19   441.2 3237.53
     446 3238.77     466 3237.75     486 3237.57   530.2 3247.06   546.3 3249.23
   556.9 3249.79   566.3 3251.77   598.5 3254.47   638.6 3262.79   652.6 3267.96
#Mann= 8 ,-1,0
       0      .1       0     160     .12       0     260      .1       0
     398    .045       0   441.2      .1       0  454.48     .04       0
   556.9     .12       0   646.9      .1       0
Bank Sta=398,441.2
XS Rating Curve= 0 ,0
Exp/Cntr(USF)=0,0
Exp/Cntr=0.3,0.1