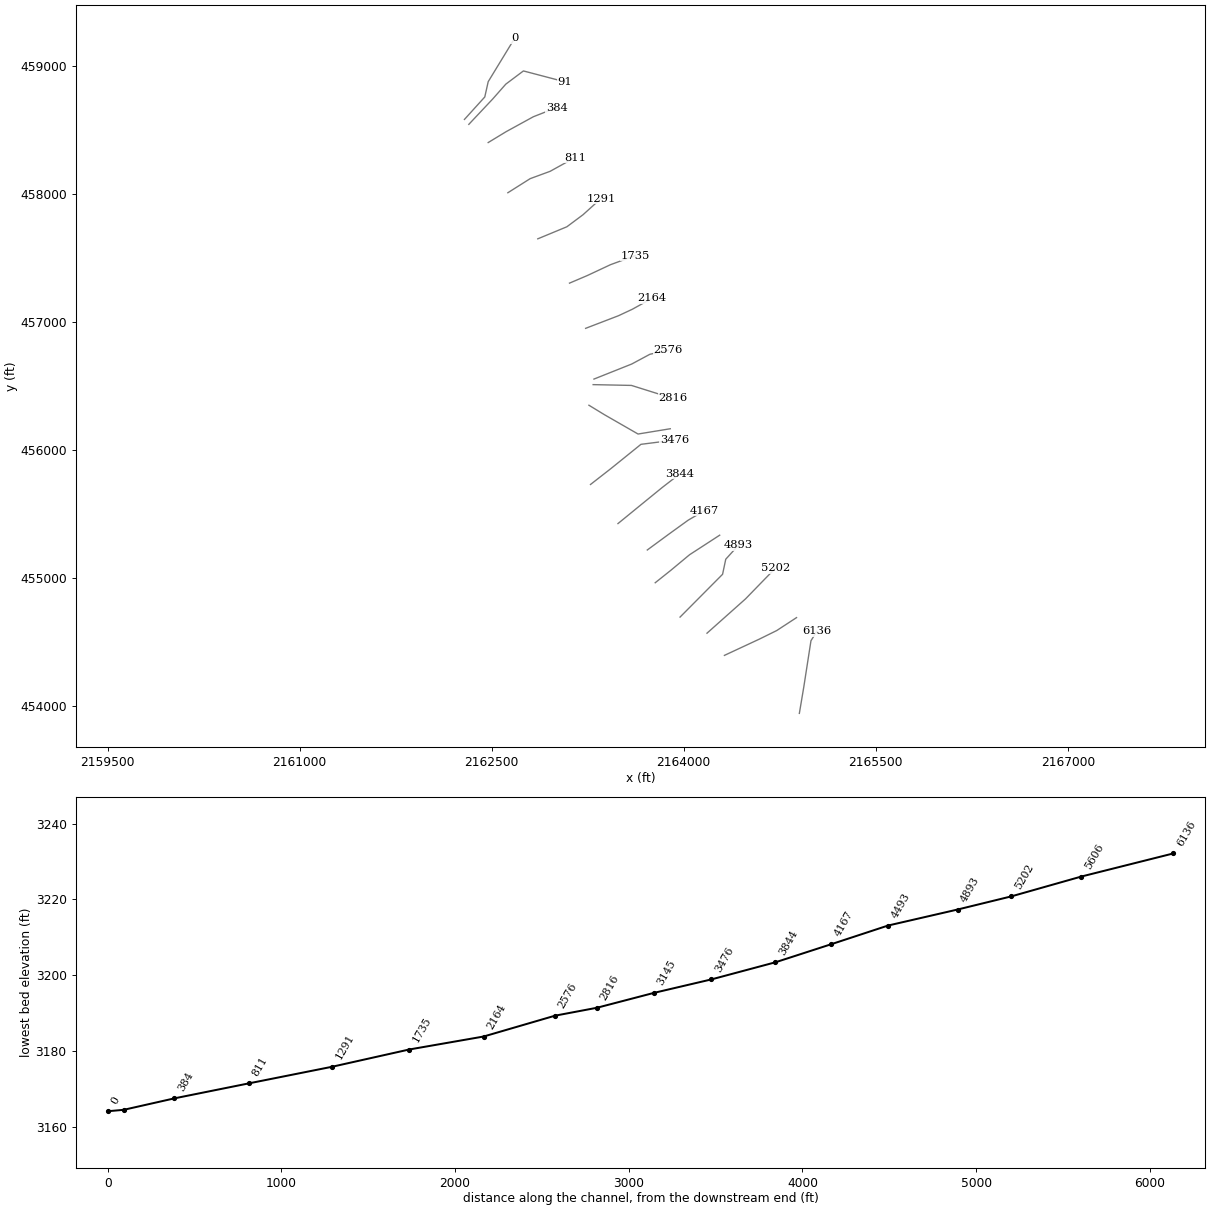
HEC-RAS study SFCRANBRYRV.prj: SFCRANBRYRV

--- SFCRANBRYRV.g01 (geometry) --- (continued)

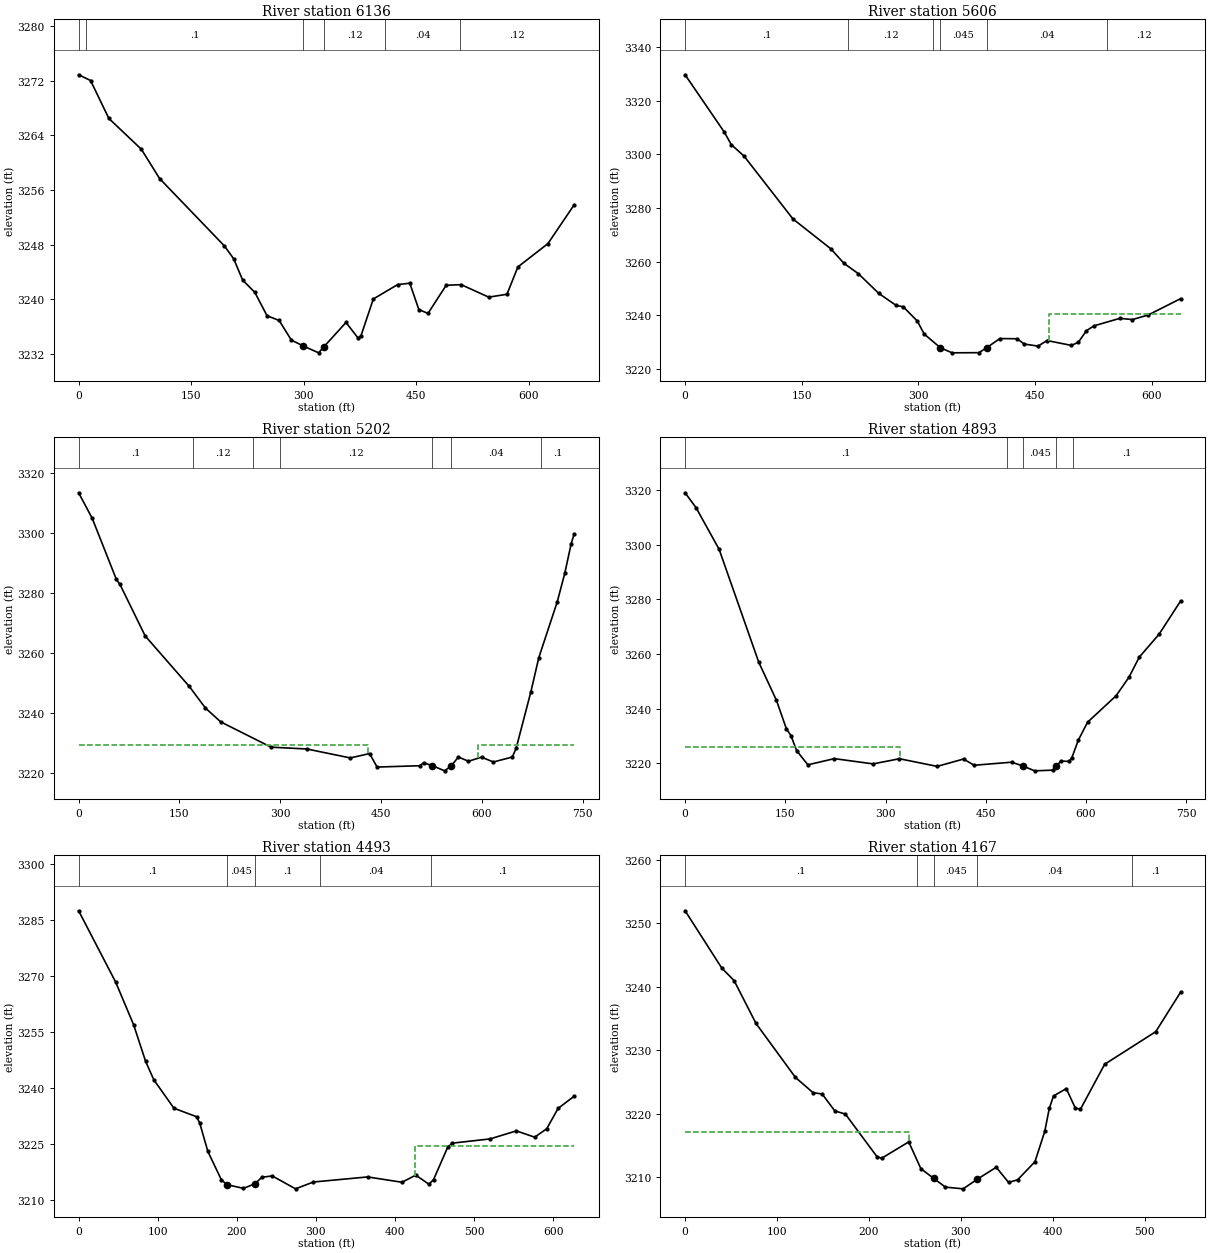
Type RM Length L Ch R = 1 ,6136    ,553.3,529.5,488.9
XS GIS Cut Line= 4
2164903.61554994453941.4589589412164938.20623064454147.060500539
2164994.30410431454508.5999410342165039.64838149454581.848388793
#Sta/Elev= 30
       0 3272.87    15.9 3272.03    40.3 3266.47    83.6 3261.96   107.9 3257.67
   194.4 3247.78   206.6 3245.92   218.7 3242.78   234.9 3240.98   251.1 3237.57
   267.3 3236.87   283.5    3234   299.7 3233.12   319.9 3232.13  327.16 3233.05
   356.4 3236.58   372.5 3234.29   376.4 3234.65   392.8 3240.02   425.2 3242.13
   441.4 3242.33   453.5 3238.46   465.7 3237.91   489.9 3242.03   509.9 3242.12
   546.6 3240.29   570.9 3240.71   585.5 3244.72   625.5 3248.13   660.5 3253.82
#Mann= 6 ,-1,0
       0     .12       0      10      .1       0   299.7    .045       0
  327.16     .12       0  408.49     .04       0  508.49     .12       0
Bank Sta=299.7,327.16
XS Rating Curve= 0 ,0
Exp/Cntr(USF)=0,0
Exp/Cntr=0.3,0.1

Type RM Length L Ch R = 1 ,5606    ,394.9,404.2,401
XS GIS Cut Line= 4
2164318.42235735454394.4100859192164588.68999616454520.259902465
2164726.91848319454588.3425901052164881.65186419454689.435065691
#Sta/Elev= 30
       0 3329.61    50.5 3308.21    59.3 3303.62    75.7 3299.34   138.7 3275.89
   187.3 3264.79   204.3 3259.35   222.6 3255.55     249 3248.17   271.3 3243.69
   280.4 3243.19   298.4 3237.91   307.4 3233.02  328.193227.915   343.2 3226.03
   377.8  3226.1  387.513227.914   404.6 3231.34   426.9 3231.28   435.8 3229.32
   453.7 3228.53   465.3 3230.61   496.7 3228.79   505.7 3230.02   515.8 3234.25
   525.4 3236.07   558.8 3238.87   575.1 3238.43   595.3 3240.13     637 3246.22
#Mann= 6 ,-1,0
       0      .1       0     210     .12       0  318.13      .1       0
  328.19    .045       0  387.51     .04       0  542.22     .12       0
#XS Ineff= 2 , 0
                          467.74         3240.33
Permanent Ineff=
       F       F
Bank Sta=328.19,387.51
XS Rating Curve= 0 ,0
Exp/Cntr(USF)=0,0
Exp/Cntr=0.3,0.1

Type RM Length L Ch R = 1 ,5202    ,290.9,309.1,325
XS GIS Cut Line= 4
2164182.25698207454567.7114726382164483.47129708454835.915999704
 2164625.8260076454982.3969337172164716.60292445455075.236962317
#Sta/Elev= 30
       0 3313.39    20.3 3304.83    56.1 3284.57    61.5 3282.87      99 3265.72
   164.6 3248.91   188.7 3241.69   211.4 3237.09   286.4 3228.66   339.5 3228.06
   404.3 3225.08     433 3226.53   444.1 3222.04   507.6 3222.48   513.4 3223.43
   526.3 3222.53   544.5 3220.78   554.6 3222.44     565 3225.39   580.1 3223.97
   599.5 3225.34   617.1 3223.72   645.3 3225.38     651 3228.26     673 3247.12
   684.7 3258.43   712.2 3277.06   723.4 3286.56   732.8 3296.29   737.4 3299.73
#Mann= 7 ,-1,0
       0      .1       0     170     .12       0     260      .1       0
     300     .12       0   526.3    .045       0   554.6     .04       0
  687.57      .1       0
#XS Ineff= 2 , 0
          431.24 3229.39  594.94         3229.55
Permanent Ineff=
       F       F
Bank Sta=526.3,554.6
XS Rating Curve= 0 ,0
Exp/Cntr(USF)=0,0
Exp/Cntr=0.3,0.1

Type RM Length L Ch R = 1 ,4893    ,408.2,400.4,373.6
XS GIS Cut Line= 4
2163971.81958391454693.5612891852164303.98057512455027.785392144
2164328.73791608455145.3827617032164429.83039167455256.790796023
#Sta/Elev= 30
       0  3318.9    16.4 3313.45    50.9 3298.26   110.3 3256.97   136.7  3243.1
   151.7 3232.62   158.4 3230.22   166.9 3224.71   183.8 3219.51   223.4 3221.77
   281.4 3219.85   320.9 3221.73   377.3 3218.94   416.8 3221.62   432.7 3219.35
     489 3220.47   506.3 3219.03   523.2 3217.31   550.3 3217.56  555.763219.021
   562.6 3220.91   574.8 3220.74   578.9 3222.05   588.6  3228.5   602.4 3235.06
   645.1 3244.72   664.5 3251.52   679.8 3258.83   709.6 3267.24   741.8 3279.39
#Mann= 5 ,-1,0
       0      .1       0  481.21     .04       0   506.3    .045       0
  555.76     .04       0  581.21      .1       0
#XS Ineff= 2 , 0
          322.11 3226.18
Permanent Ineff=
       F       F
Bank Sta=506.3,555.76
XS Rating Curve= 0 ,0
Exp/Cntr(USF)=0,0
Exp/Cntr=0.3,0.1

Type RM Length L Ch R = 1 ,4493    ,306.1,325.8,311.6
XS GIS Cut Line= 4
2163777.88707972 454961.765816252163899.61067278455058.732068344
2164046.09160679455180.4556613972164281.28634591455333.125930649
#Sta/Elev= 30
       0 3287.54    46.8 3268.45    69.5 3257.03    84.7 3247.21    95.1 3242.26
   120.5 3234.67   149.2 3232.38   153.1 3230.69   163.4 3223.08   180.5 3215.48
   187.6 3214.19   208.4 3213.21   223.1 3214.45   231.6 3216.18   244.8 3216.54
   274.2 3213.08   296.9 3214.91   365.5 3216.27   408.8 3214.84   426.2 3216.75
   442.9 3214.31   448.7 3215.55   466.7 3224.27   472.6 3225.32   520.2 3226.45
   553.4  3228.6   576.6 3226.91   591.8 3229.17   606.1  3234.6   626.5  3237.9
#Mann= 5 ,-1,0
       0      .1       0   187.6    .045       0   223.1      .1       0
  305.62     .04       0  446.08      .1       0
#XS Ineff= 2 , 0
                          424.73         3224.59
Permanent Ineff=
       F       F
Bank Sta=187.6,223.1
XS Rating Curve= 0 ,0
Exp/Cntr(USF)=0,0
Exp/Cntr=0.3,0.1

Type RM Length L Ch R = 1 ,4167    ,320,322.5,324.9
XS GIS Cut Line= 4
2163715.99372732455217.591672836 2163887.2320023455343.441489383
2164035.77604806455450.7233002092164159.56275286455522.932211342
#Sta/Elev= 30
       0    3252    39.9 3242.97    53.3    3241    77.1 3234.25     120 3225.74
   139.2 3223.33   149.1 3223.12   162.9 3220.45   174.4 3219.95   208.7 3213.25
   213.7 3212.98   243.3 3215.57   256.5 3211.35  270.363209.828   283.2 3208.44
   302.5 3208.17     318  3209.7   338.5 3211.57   351.9 3209.18   361.7 3209.59
   380.6 3212.44   391.3 3217.24   396.2 3220.84   400.8 3222.81   414.7 3223.97
   424.4 3220.94     430 3220.69   456.4  3227.8     512 3232.94   539.1 3239.18
#Mann= 5 ,-1,0
       0      .1       0  252.51     .04       0  270.36    .045       0
     318     .04       0  485.74      .1       0
#XS Ineff= 2 , 0
          243.56 3217.18
Permanent Ineff=
       F       F
Bank Sta=270.36,318
XS Rating Curve= 0 ,0
Exp/Cntr(USF)=0,0
Exp/Cntr=0.3,0.1

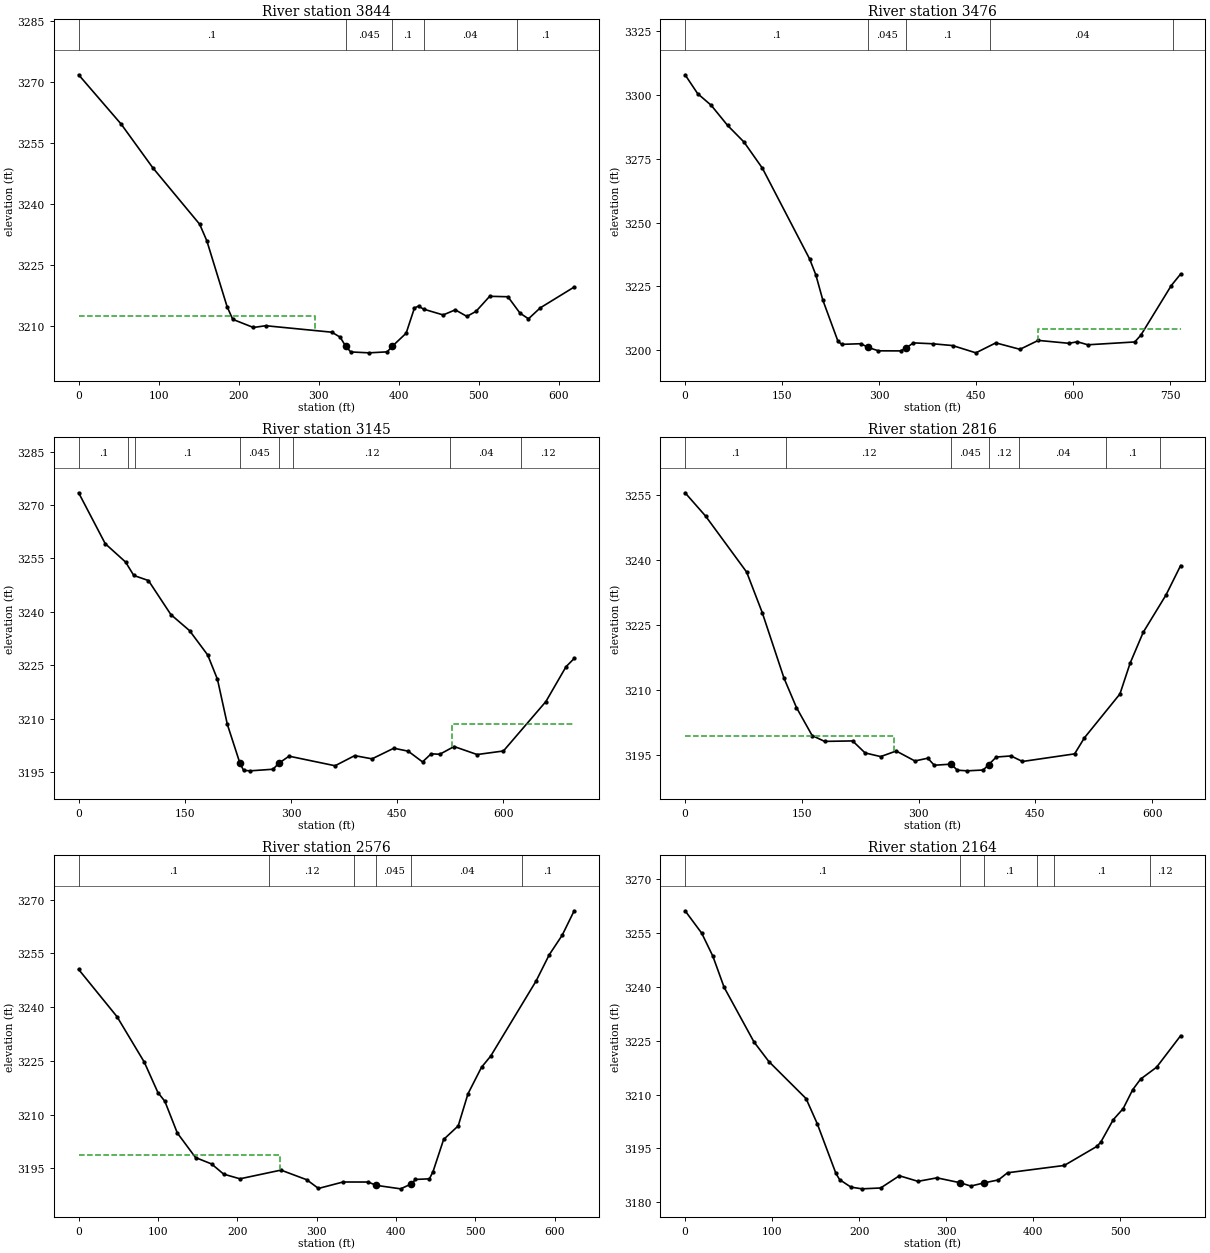
Type RM Length L Ch R = 1 ,3844    ,369.4,368.5,369.1
XS GIS Cut Line= 4
2163486.98832344455423.9028475022163689.17327462455588.951787235
2163833.59109688455706.5491567952163969.75647216455811.767855875
#Sta/Elev= 30
       0 3271.69    53.2 3259.56    92.7 3248.84   151.3 3234.96   160.2 3230.91
   185.5 3214.75   192.6 3211.61   218.4 3209.61   233.9 3210.04   316.5 3208.45
   326.8 3207.23   333.83205.001   340.1  3203.6   362.8 3203.38   385.6 3203.62
  392.043205.002   409.3  3208.2   419.7 3214.41   424.8 3214.87     431 3214.12
   455.6 3212.69   470.7 3213.94   485.2 3212.33   496.6 3213.56   513.7 3217.27
   536.5 3217.16   551.6 3213.13   562.2 3211.74   576.9 3214.43   619.3 3219.54
#Mann= 5 ,-1,0
       0      .1       0   333.8    .045       0  392.04      .1       0
     431     .04       0  547.24      .1       0
#XS Ineff= 2 , 0
          294.94 3212.36
Permanent Ineff=
       F       F
Bank Sta=333.8,392.04
XS Rating Curve= 0 ,0
Exp/Cntr(USF)=0,0
Exp/Cntr=0.3,0.1

Type RM Length L Ch R = 1 ,3476    ,373.4,330.9,286.3
XS GIS Cut Line= 4
2163272.42470179455729.2433860082163431.28430628455853.030090808
 2163666.4790454456042.8363715012163926.43112548456075.846159447
#Sta/Elev= 30
       0 3307.96    19.4 3300.56    40.3 3295.99    65.6 3288.11      91 3281.57
   119.5 3271.28   192.4  3235.7   202.1 3229.38   212.8 3219.57   236.3 3203.34
     242 3202.19   271.7 3202.44   282.93200.976   298.8 3199.65     333 3199.62
   341.5  3200.8   352.9 3202.77   382.4 3202.42   413.3 3201.72   449.3 3198.86
   480.1 3202.77   517.4 3200.24   545.7 3203.74   593.1  3202.6   606.1  3203.2
   622.3 3202.02   694.8 3203.13     704 3205.71   751.3 3225.28   765.7 3229.79
#Mann= 5 ,-1,0
       0      .1       0   282.9    .045       0   341.5      .1       0
  471.39     .04       0  753.62     .12       0
#XS Ineff= 2 , 0
                          544.77         3208.21
Permanent Ineff=
       F       F
Bank Sta=282.9,341.5
XS Rating Curve= 0 ,0
Exp/Cntr(USF)=0,0
Exp/Cntr=0.3,0.1

Type RM Length L Ch R = 1 ,3145    ,319.9,329.1,331.4
XS GIS Cut Line= 4
2163260.04603131456348.1769100062163381.76962436456273.904887127
2163643.78481619 456123.297729622163895.48444928456164.559964554
#Sta/Elev= 30
       0 3273.43    37.6 3259.12    66.3 3253.97    77.9  3250.2    98.6 3248.77
   130.3  3239.2   156.6 3234.71   182.3 3227.85   196.1    3221     210 3208.38
  227.813197.447     233 3195.43   242.3  3195.3   274.6 3195.75   282.6 3197.41
   297.2 3199.42   362.2 3196.73   389.9 3199.57   414.4 3198.67   445.2 3201.66
   465.5 3200.82   485.7 3197.81   497.9 3200.08   510.1 3199.96   530.3 3202.13
   562.8 3199.88     600 3200.88     660 3214.78   688.4 3224.56   699.9 3226.87
#Mann= 8 ,-1,0
       0      .1       0      70     .08       0      80      .1       0
  227.81    .045       0   282.6      .1       0  302.59     .12       0
  524.81     .04       0  624.81     .12       0
#XS Ineff= 2 , 0
                          527.96         3208.55
Permanent Ineff=
       F       F
Bank Sta=227.81,282.6
XS Rating Curve= 0 ,0
Exp/Cntr(USF)=0,0
Exp/Cntr=0.3,0.1

Type RM Length L Ch R = 1 ,2816    ,210.7,240.3,263.2
XS GIS Cut Line= 4
2163293.05581926456509.0996262462163592.20702252456502.910291006
2163736.62484479456457.521832579  2163914.052455456401.817815419
#Sta/Elev= 30
       0 3255.57    26.5 3250.15    79.1 3237.25    99.1  3227.9   127.1 3212.75
   143.1 3205.96   163.2 3199.51   179.2 3198.16   215.2 3198.27   231.2  3195.5
   251.2 3194.65   271.2 3195.94   295.2 3193.64   311.8 3194.28   320.1 3192.65
     342 3192.91   349.5 3191.52   362.1 3191.36     383 3191.55   389.9 3192.78
   399.8 3194.55   418.6  3194.8   433.4 3193.52   500.4 3195.28     513 3198.99
   558.6 3209.11   571.7 3216.22   588.5 3223.34   617.8 3231.97   636.6 3238.77
#Mann= 7 ,-1,0
       0      .1       0     130     .12       0     342    .045       0
   389.9     .12       0  429.22     .04       0   540.6      .1       0
   610.6     .12       0
#XS Ineff= 2 , 0
          267.99 3199.44
Permanent Ineff=
       F       F
Bank Sta=342,389.9
XS Rating Curve= 0 ,0
Exp/Cntr(USF)=0,0
Exp/Cntr=0.3,0.1

Type RM Length L Ch R = 1 ,2576    ,412.1,411.8,406.4
XS GIS Cut Line= 4
 2163299.2451545456552.4249729262163594.27013427456670.022342485
2163736.62484479456746.3574771122163878.97955531456777.304153312
#Sta/Elev= 30
       0 3250.53    48.4 3237.34    82.8 3224.64     100 3216.14   108.7 3213.73
   124.4 3204.88   147.4 3198.01   167.6 3196.23   182.9 3193.38   203.4 3192.08
   255.1 3194.51   287.6 3191.82   302.4 3189.39   333.4 3191.19   365.1 3191.18
   375.1 3190.26     406 3189.28  419.613190.673   424.7  3191.9   442.3 3192.08
   446.8 3194.07   460.2 3203.06   478.6 3206.86   490.9 3215.81     508 3223.23
   519.6 3226.35   576.9 3247.34   593.3  3254.6   609.7 3260.08   624.8  3266.9
#Mann= 6 ,-1,0
       0      .1       0     240     .12       0   347.6     .04       0
   375.1    .045       0  419.61     .04       0  559.13      .1       0
#XS Ineff= 2 , 0
          254.13 3198.64
Permanent Ineff=
       F       F
Bank Sta=375.1,419.61
XS Rating Curve= 0 ,0
Exp/Cntr(USF)=0,0
Exp/Cntr=0.3,0.1

Type RM Length L Ch R = 1 ,2164    ,426.5,428.7,415.2
XS GIS Cut Line= 4
 2163234.3717518456948.7716629232163491.11454694457047.342557486
2163598.85482704 457097.774177962163752.44203485457182.590994211
#Sta/Elev= 30
       0 3261.16    19.1 3254.92    31.9 3248.52    44.8 3239.88    79.1 3224.67
    96.2 3219.21     139 3208.89   151.9 3201.87   173.3 3188.06   177.6 3186.32
   190.6 3184.24   203.3 3183.77   224.7 3184.01   246.2 3187.41   267.6 3185.86
   289.4 3186.83   316.3 3185.45   328.3 3184.54   343.4 3185.42   360.1 3186.26
   370.5 3188.24   435.7 3190.28   473.2 3195.59   477.7 3196.79     492 3203.02
   503.4 3206.11   514.3 3211.35   523.4 3214.32   541.7  3217.6   569.4 3226.39
#Mann= 6 ,-1,0
       0      .1       0   316.3    .045       0   343.4      .1       0
  403.97     .04       0  423.97      .1       0  533.97     .12       0
Bank Sta=316.3,343.4
XS Rating Curve= 0 ,0
Exp/Cntr(USF)=0,0
Exp/Cntr=0.3,0.1

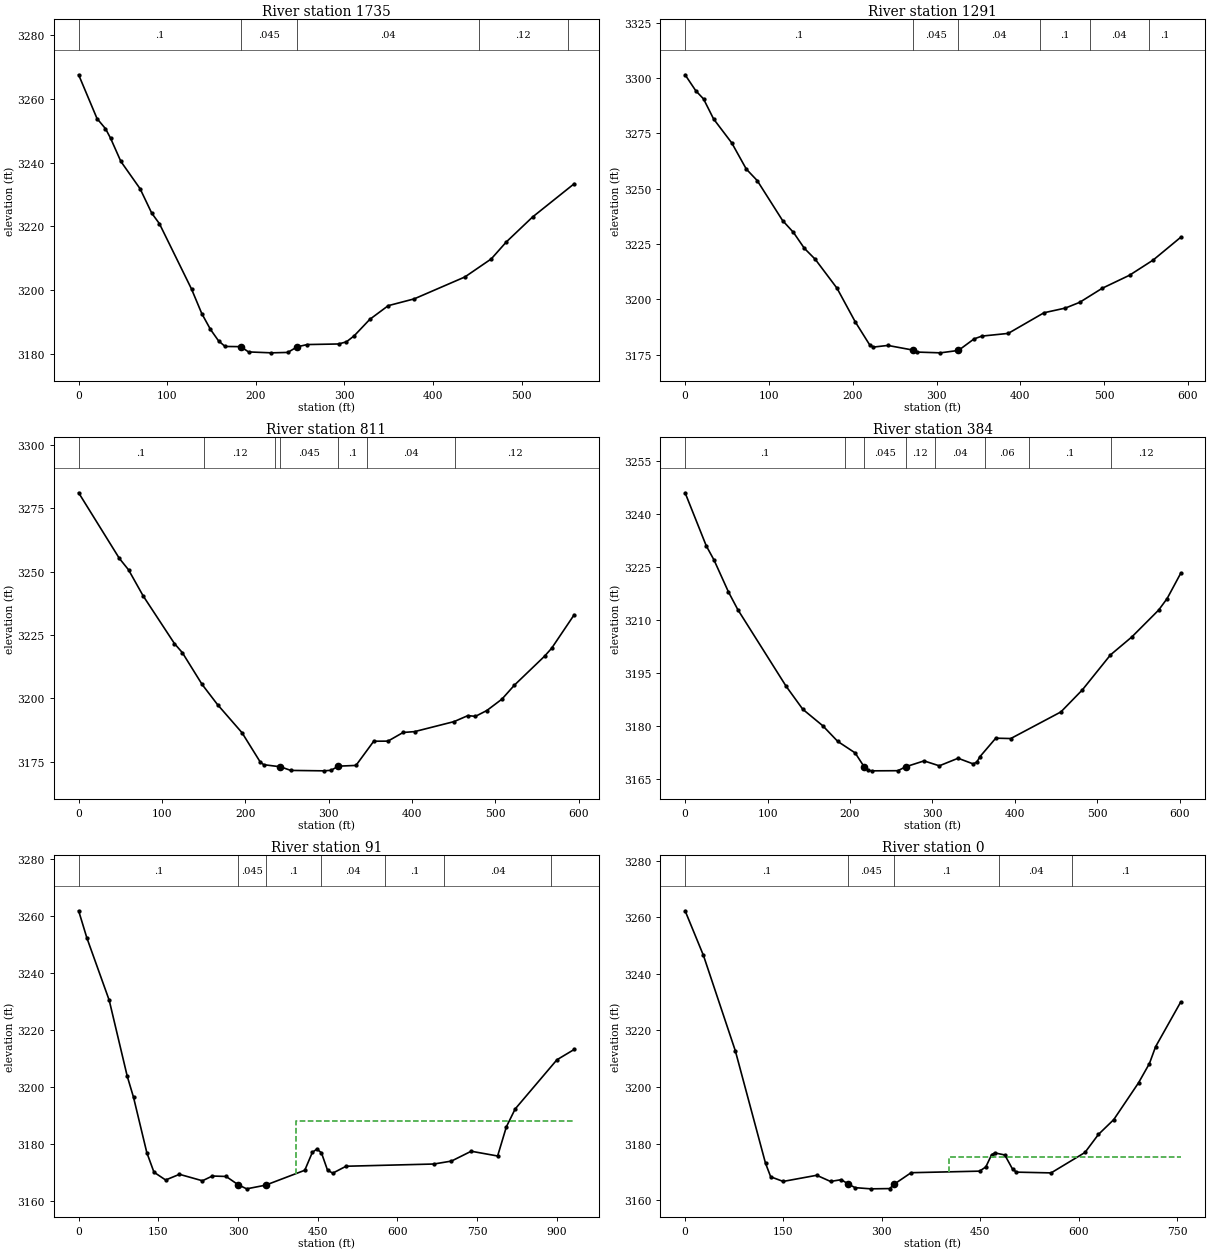
Type RM Length L Ch R = 1 ,1735    ,428.7,444.1,444.6
XS GIS Cut Line= 4
2163108.29270061 457301.793006242163248.12583011457361.394012255
2163429.22119454457446.2108285072163624.07063728457517.273566447
#Sta/Elev= 30
       0 3267.58    20.8 3253.82    30.3 3250.68      36 3247.71    47.7 3240.38
    69.4 3231.82    82.5 3224.18    91.2 3220.86   127.5 3200.32     139 3192.67
   148.8  3187.7   157.9 3184.12   165.3 3182.34     183 3182.28   191.8 3180.63
   217.5 3180.34   236.1 3180.47   246.73182.225   258.1 3182.94   293.4 3183.12
   302.3 3183.79   311.1 3185.69   328.7 3190.85   349.5 3195.14   378.8 3197.27
     436 3204.14   465.8 3209.81   482.9 3215.16   512.4 3222.95   559.4 3233.39
#Mann= 5 ,-1,0
       0      .1       0     183    .045       0   246.7     .04       0
  451.98     .12       0  551.98      .1       0
Bank Sta=183,246.7
XS Rating Curve= 0 ,0
Exp/Cntr(USF)=0,0
Exp/Cntr=0.3,0.1

Type RM Length L Ch R = 1 ,1291    ,491.1,479.8,466.3
XS GIS Cut Line= 4
2162860.71929101457647.9373104022163087.66158315457741.923512195
2163213.74063433457835.9097139872163353.57376383457961.988765172
#Sta/Elev= 30
       0 3301.52    12.8 3294.27      22  3290.6      34 3281.54    55.7 3270.69
      73 3258.88      86  3253.7   116.3 3235.61   129.3 3230.22   142.3 3223.04
   155.3 3218.07   181.2 3205.02   202.9 3189.86   220.2 3179.39   224.5 3178.38
   241.9 3179.13   271.4 3177.06   276.2 3176.13   304.6 3175.78   326.1 3176.87
   344.8 3182.09   354.1 3183.35   385.5 3184.57   428.2 3193.91   453.7 3196.03
   470.7 3198.61   497.7 3204.99   530.2 3210.87   558.5 3217.76   591.2 3228.01
#Mann= 6 ,-1,0
       0      .1       0   271.4    .045       0   326.1     .04       0
  422.89      .1       0  482.89     .04       0  552.89      .1       0
Bank Sta=271.4,326.1
XS Rating Curve= 0 ,0
Exp/Cntr(USF)=0,0
Exp/Cntr=0.3,0.1

Type RM Length L Ch R = 1 ,811     ,420.8,427.7,433.7
XS GIS Cut Line= 4
2162626.89995972458007.835692875  2162801.118285458117.868319364
2162956.99783919458175.1769789932163151.84728193458282.917259097
#Sta/Elev= 30
       0 3281.16    48.8 3255.29    59.9 3250.75    77.4 3240.48     115 3221.64
   124.5 3218.05   148.2  3205.5   166.7 3197.55   196.2  3186.4   217.8 3174.97
   222.1 3173.82   242.2 3172.99   254.6 3171.56   294.5 3171.39   303.1 3171.61
   311.6 3173.23   332.9 3173.53   354.2 3183.08   371.3 3183.12   389.5 3186.54
   403.2 3186.87   450.7 3190.83   467.2 3193.19   476.3  3192.9     490 3195.21
   508.1  3199.7   523.1 3205.23   559.2 3216.63   567.7 3219.76   594.8    3233
#Mann= 7 ,-1,0
       0      .1       0     150     .12       0  236.06      .1       0
   242.2    .045       0   311.6      .1       0  346.06     .04       0
  452.14     .12       0
Bank Sta=242.2,311.6
XS Rating Curve= 0 ,0
Exp/Cntr(USF)=0,0
Exp/Cntr=0.3,0.1

Type RM Length L Ch R = 1 ,384     ,281.3,292.3,306
XS GIS Cut Line= 4
2162473.31275192458399.8269247412162613.14588141458484.643740993
2162826.33409524458601.5534066372163007.42945966458672.616144577
#Sta/Elev= 30
       0 3246.04    25.7 3231.03    35.1 3227.03    52.6 3218.01    63.9 3213.03
   122.5 3191.37   142.8 3184.84     167 3180.19   185.2 3175.76   206.3 3172.51
   217.2  3168.6   221.7  3167.6   226.3 3167.44   258.2 3167.48   267.4 3168.57
   289.9 3170.25   308.4 3168.86   331.2    3171   349.5  3169.4     354 3169.94
   357.7 3171.44   376.9 3176.67   395.1 3176.57   455.9 3184.09   481.9 3190.31
   516.1 3200.22   541.9 3205.27   574.5 3212.88   584.8 3216.14   601.2 3223.24
#Mann= 8 ,-1,0
       0      .1       0  193.55     .12       0   217.2    .045       0
   267.4     .12       0  303.55     .04       0  363.55     .06       0
  416.69      .1       0  516.69     .12       0
Bank Sta=217.2,267.4
XS Rating Curve= 0 ,0
Exp/Cntr(USF)=0,0
Exp/Cntr=0.3,0.1

Type RM Length L Ch R = 1 ,91      ,75.8,91.3,110.1
XS GIS Cut Line= 5
 2162322.0178905458541.952400622 2162507.6979477458739.094189747
2162610.85353503458856.0038553922162748.39431814458959.159442725
2163071.61515845458874.342626473
#Sta/Elev= 30
       0 3261.87    15.4 3252.42    57.6 3230.48    91.5 3203.87   103.3 3196.51
   128.3 3177.14   141.8 3170.24   163.8 3167.51   189.8  3169.5     233 3167.24
   251.7  3168.9   277.6 3168.75   300.3 3165.85   316.3 3164.41     352  3165.7
   425.7 3170.92   439.9 3177.18   448.5 3178.37   457.1 3177.02   468.5 3170.95
   478.4 3169.91   503.4 3172.33   668.7 3173.11   701.8 3174.14     739 3177.59
   788.7 3175.92   805.2 3186.16   821.7  3192.4   900.3 3209.64   932.8 3213.26
#Mann= 7 ,-1,0
       0      .1       0   300.3    .045       0     352      .1       0
  456.73     .04       0  576.73      .1       0  688.66     .04       0
  888.66      .1       0
#XS Ineff= 2 , 0
                           408.6         3188.07
Permanent Ineff=
       F       F
Bank Sta=300.3,352
XS Rating Curve= 0 ,0
Exp/Cntr(USF)=0,0
Exp/Cntr=0.3,0.1

Type RM Length L Ch R = 1 ,0       ,,,
XS GIS Cut Line= 4
2162287.79315897458580.4408964292162446.65276346458755.805394895
2162473.47321616458875.4658762022162679.78439083459213.816202654
#Sta/Elev= 30
       0 3262.27      28 3246.48    76.6 3212.79   122.6 3173.08   130.5 3168.29
   149.5 3166.66   200.7 3168.83   221.7 3166.65     238 3167.27  248.893165.737
   259.1 3164.46   283.1 3164.04   311.8 3164.13  319.123165.739   344.6 3169.74
     449 3170.29   458.5 3171.79   467.2 3176.03     472 3176.74   487.4 3176.01
   499.2 3171.02   505.1 3169.94     558 3169.67   609.6 3176.88   630.2 3183.27
   653.5 3188.49   691.3 3201.49   707.9  3208.3   717.3 3214.24   755.5 3229.99
#Mann= 5 ,-1,0
       0      .1       0  248.89    .045       0  319.12      .1       0
  479.25     .04       0  589.25      .1       0
#XS Ineff= 2 , 0
                           402.2         3175.27
Permanent Ineff=
       F       F
Bank Sta=248.89,319.12
XS Rating Curve= 0 ,0
Exp/Cntr(USF)=0,0
Exp/Cntr=0.3,0.1
LCMann Table=0

Chan Stop Cuts=-1
Use User Specified Reach Order=0
Composite Channel Slope=5